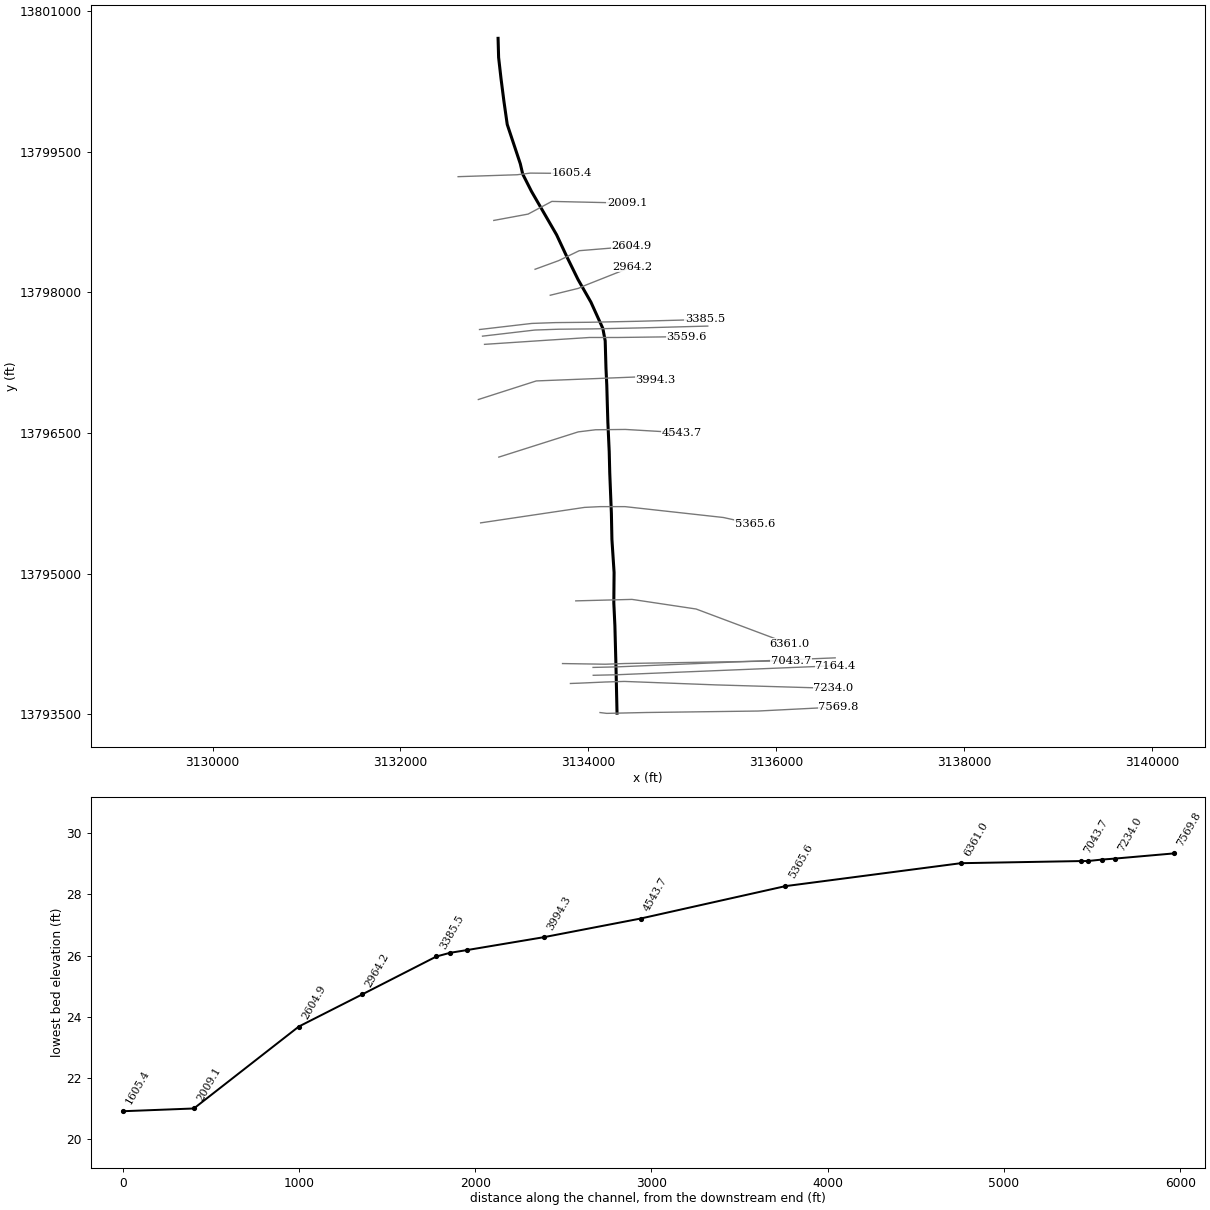
--- C123-00-00.PRJ (project) ---

Proj Title=C123-00-00
Current Plan=p02
Default Exp/Contr=0.3,0.1
English Units
Geom File=g01
Geom File=g02
Flow File=f01
Flow File=f02
Plan File=p01
Plan File=p02
Y Axis Title=Elevation
X Axis Title(PF)=Main Channel Distance
X Axis Title(XS)=Station
BEGIN DESCRIPTION:
Sims Bayou Watershed
Tributary 10.77 to Sims Bayou
HCFCD Unit C123-00-00
Flood Hazard Model
10, 2, 1, 0.2% Event
Filename C123-00-00.prj
Prepared by:  Watershed Concepts  Date:
Reviewed by:                      Date:
STATUS FINAL
END DESCRIPTION:
DSS File=dss
DSS Export Rating Curves= 0
DSS Export Rating Curve Sorted= 0
DSS Export Volume Flow Curves= 0
DXF OffsetX= 0
DXF OffsetY= 0
DXF ScaleX= 1
DXF ScaleY= 10

--- C123-00-00.p02 (plan) ---

Plan Title=Effective Floodway 2015
Program Version=4.10
Short Identifier=RiskMAP FW
Geom File=g02
Flow File=f02
Subcritical Flow
K Sum by GR= 0
Std Step Tol= 0.01
Critical Tol= 0.01
Num of Std Step Trials= 20
Max Error Tol= 0.3
Flow Tol Ratio= 0.001
Split Flow NTrial= 30
Split Flow Tol= 0.02
Split Flow Ratio= 0.02
Log Output Level= 0
Friction Slope Method= 1
Unsteady Friction Slope Method= 2
Unsteady Bridges Friction Slope Method= 1
Parabolic Critical Depth
Global Vel Dist= 0 , 0 , 0
Global Log Level= 0
CheckData=True
Encroach Param=-1 ,0,0, 2
Encroach River=C123-00-00
Encroach Reach=Reach - 1
Encroach Node=7569.8
       1  4952.5  5045.2
Encroach Node=7234.0
       1    4958  5045.3
Encroach Node=7164.4
       1    4958  5045.3
Encroach Node=7122.4
       1    4958  5045.3
Encroach Node=7080.4
       1    4958  5045.3
Encroach Node=7043.7
       1    4955  5047.8
Encroach Node=6361.0
       1    4955  5047.8
Encroach Node=5365.6
       1  4963.1  5046.2
Encroach Node=4543.7
       1  4960.5  5038.7
Encroach Node=3994.3
       1 4970.85 5052.35
Encroach Node=3559.6
       1 4970.85 5052.35
Encroach Node=3463.0
       1  4970.9  5052.4
Encroach Node=3424.2
       1    4970  5052.4
Encroach Node=3385.5
       1  4970.9  5052.4
Encroach Node=2964.2
       1  4964.1  5033.8
Encroach Node=2604.9
       1  4964.1  5033.8
Encroach Node=2009.1
       1  4968.5  5045.1
Encroach Node=1605.4
       1  4968.5  5045.1
Encroach Node=1582.9
       1  4968.5  5045.1
Encroach Node=1560.8
       1  4968.5  5045.1
Encroach Node=1538.7
       1  4968.5  5045.1
Encroach Node=1277.4
       1 4968.49 5045.09
Encroach Node=871.7
       1  4943.3  5071.3
Encroach Node=773.2
       1  4943.3  5071.3
Encroach Node=715.7
       1  4943.3  5071.3
Encroach Node=658.2
       1  4943.3  5071.3
Encroach Node=328.2
       1    4941  5059.8
Encroach Reach=C123-00-00_0003
Encroach Node=7569.8
       1  4952.5  5045.2
Encroach Node=7234.0
       1    4958  5045.3
Encroach Node=7164.4
       1    4958  5045.3
Encroach Node=7122.4
       1    4958  5045.3
Encroach Node=7080.4
       1    4958  5045.3
Encroach Node=7043.7
       1    4955  5047.8
Encroach Node=6361.0
       1    4955  5047.8
Encroach Node=5365.6
       1  4963.1  5046.2
Encroach Node=4543.7
       1  4960.5  5038.7
Encroach Node=3994.3
       1 4970.85 5052.35
Encroach Node=3559.6
       1 4970.85 5052.35
Encroach Node=3463.0
       1  4970.9  5052.4
Encroach Node=3424.2
       1    4970  5052.4
Encroach Node=3385.5
       1  4970.9  5052.4
Encroach Node=2964.2
       1  4964.1  5033.8
Encroach Node=2604.9
       1  4964.1  5033.8
Encroach Node=2009.1
       1  4968.5  5045.1
Encroach Node=1605.4
       1  4968.5  5045.1
Encroach Node=1582.9
       1  4968.5  5045.1
Encroach Node=1560.8
       1  4968.5  5045.1
Encroach Node=1538.7
       1  4968.5  5045.1
Encroach Node=1277.4
       1 4968.49 5045.09
Encroach Node=871.7
       1  4943.3  5071.3
Encroach Node=773.2
       1  4943.3  5071.3
Encroach Node=715.7
       1  4943.3  5071.3
Encroach Node=658.2
       1  4943.3  5071.3
Encroach Node=328.2
       1    4941  5059.8
BEGIN DESCRIPTION:
FEMA Effective Risk Map Study Floodway May 02, 2019
END DESCRIPTION:
Computation Interval=1HOUR
Output Interval=1HOUR
Run HTab= 0
Run UNet= 0
Run PostProcess= 0
Run WQNet= 0
UNET Theta= 1
UNET Theta Warmup= 1
UNET ZTol= 0.02
UNET ZSATol= 0.1
UNET MxIter= 20
UNET MaxInSteps= 20
UNET DtIC= 0
UNET DtMin= 0
UNET MaxCRTS= 20
UNET WFStab= 2
UNET SFStab= 1
UNET WFX= 1
UNET SFX= 1
UNET DSS MLevel= 4
UNET DZMax Abort= 100
UNET Convert EG Bridges=-1
UNET Use Existing IB Tables=-1
UNET Froude Reduction=False
UNET Froude Limit= 1
UNET Froude Power= 10
UNET Time Slicing=0,0, 5
UNET Junction Losses=0
Instantaneous Interval=1HOUR
DSS File=dss
Write IC File= 0
IC Time=0,,
Write IC File at Sim End=0
Echo Input=False
Echo Parameters=False
Echo Output=False
Write Detailed= 0
WQ AD Non Conservative
WQ ULTIMATE=-1
WQ Max Comp Step=1HOUR
WQ Output Interval=15MIN
WQ Output Selected Increments= 0
WQ Output face flow=0
WQ Output face velocity=0
WQ Output face area=0
WQ Output face dispersion=0
WQ Output cell volume=0
WQ Output cell surface area=0
WQ Output cell continuity=0
WQ Output cumulative cell continuity=0
WQ Output face conc=0
WQ Output face dconc_dx=0
WQ Output face courant=0
WQ Output face peclet=0
WQ Output face adv mass=0
WQ Output face disp mass=0
WQ Output cell mass=0
WQ Output cell source sink temp=0
WQ Output cell source sink nsm=0
WQ Output MaxMinRange=-1
WQ Daily Max Min Mean=-1
WQ Daily Range=0
WQ Daily Time=0
WQ Create Restart=0
WQ Fixed Restart=0
WQ System Summary=0
WQ Use Fixed Temperature=0
Sorting and Armoring Iterations= 10
XS Update Threshold= 0.02
Hydraulics Update Threshold= 0.02
Energy Slope Method= 1
Volume Change Method= 0
XS Weighting Method= 0
Number of US Weighted Cross Sections= 1
Number of DS Weighted Cross Sections= 1
Upstream XS Weight=0.25
Main XS Weight=0.5
Downstream XS Weight=0.25
Number of DS XS's Weighted with US Boundary= 1
Upstream Boundary Weight= 1
Weight of XSs Associated with US Boundary= 0
Number of US XS's Weighted with DS Boundary= 1
Downstream Boundary Weight= 0.5
Weight of XSs Associated with DS Boundary= 0.5
Sediment Output Level= 4
Mass or Volume Output= 0
Output Increment Type= 1
Profile and TS Output Increment= 10
XS Output Flag= 0
XS Output Increment= 10
Disregard all LS=0
Disregard all Conn=0
Disregard all Breaches=0
Disregard all Pumps=0

--- C123-00-00.p01 (plan) ---

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Plan Title=Effective Multi-Profile 2015
Short Identifier=RiskMAP MP
Geom File=g01
Flow File=f01
Encroach Param=-1 ,0,0, 0
FEMA Effective Risk Map Study Multi-Profile May 02, 2019

--- C123-00-00.f02 (steady flow) ---

Flow Title=Effective Floodway 2015
Program Version=4.10
Number of Profiles= 2
Profile Names=1PCT_100yr,Floodway
River Rch & RM=C123-00-00,C123-00-00_0003 ,7569.8
     700     700
River Rch & RM=C123-00-00,C123-00-00_0003 ,7164.4
     953     953
River Rch & RM=C123-00-00,C123-00-00_0003 ,3424.2
    1221    1221
River Rch & RM=C123-00-00,C123-00-00_0003 ,1560.8
    1424    1424
River Rch & RM=C123-00-00,C123-00-00_0003 ,715.7
    1451    1451
Boundary for River Rch & Prof#=C123-00-00,C123-00-00_0003 , 1
Up Type= 0
Dn Type= 3
Dn Slope=0.0024
Boundary for River Rch & Prof#=C123-00-00,C123-00-00_0003 , 2
Up Type= 0
Dn Type= 1
Dn Known WS=25.81
DSS Import GetInterval= 0
DSS Import GetPeak= 0
DSS Import FillOption= 0

--- C123-00-00.f01 (steady flow) ---

Flow Title=Effective Multi-Profile 2015
Program Version=4.10
Number of Profiles= 6
Profile Names=10PCT_10yr,4PCT_25yr,2PCT_50yr,1PCT_100yr,1PCT_Plus,0.2PCT_500yr
River Rch & RM=C123-00-00,C123-00-00_0003 ,7569.8
     386     493     593     700     841    1014
River Rch & RM=C123-00-00,C123-00-00_0003 ,7164.4
     525     670     806     953    1144    1381
River Rch & RM=C123-00-00,C123-00-00_0003 ,3424.2
     673     859    1033    1221    1465    1768
River Rch & RM=C123-00-00,C123-00-00_0003 ,1560.8
     785    1001    1204    1424    1709    2061
River Rch & RM=C123-00-00,C123-00-00_0003 ,715.7
     800    1021    1227    1451    1741    2101
Boundary for River Rch & Prof#=C123-00-00,C123-00-00_0003 , 1
Up Type= 0
Dn Type= 3
Dn Slope=0.0024
Boundary for River Rch & Prof#=C123-00-00,C123-00-00_0003 , 2
Up Type= 0
Dn Type= 3
Dn Slope=0.0024
Boundary for River Rch & Prof#=C123-00-00,C123-00-00_0003 , 3
Up Type= 0
Dn Type= 3
Dn Slope=0.0024
Boundary for River Rch & Prof#=C123-00-00,C123-00-00_0003 , 4
Up Type= 0
Dn Type= 3
Dn Slope=0.0024
DSS Import GetInterval= 0
DSS Import GetPeak= 0
DSS Import FillOption= 0

--- C123-00-00.g02 (geometry) ---

Geom Title=C123-00-00 2015
Program Version=4.10

River Reach=C123-00-00      ,C123-00-00_0003
Reach XY= 28
        3134306.     13793511.01       3134294.8     13794007.28
      3134283.28     13794441.95      3134271.77     13794686.64
      3134274.65     13795011.92      3134251.62     13795363.12
      3134245.86     13795642.34      3134228.59     13796071.26
      3134222.83     13796298.67      3134208.44     13796612.45
      3134202.68     13796805.32      3134196.92      13797009.7
      3134188.29     13797191.05        3134180.       13797482.
      3134154.75       13797615.       3134028.5       13797894.
        3133891.       13798136.      3133774.75       13798373.
      3133662.75       13798613.        3133395.       13799077.
        3133302.       13799261.      3133283.75       13799339.
        3133276.       13799372.      3133137.25       13799790.
       3133101.5       13800041.      3133071.37     13800276.95
      3133045.47     13800504.37      3133039.71     13800708.75

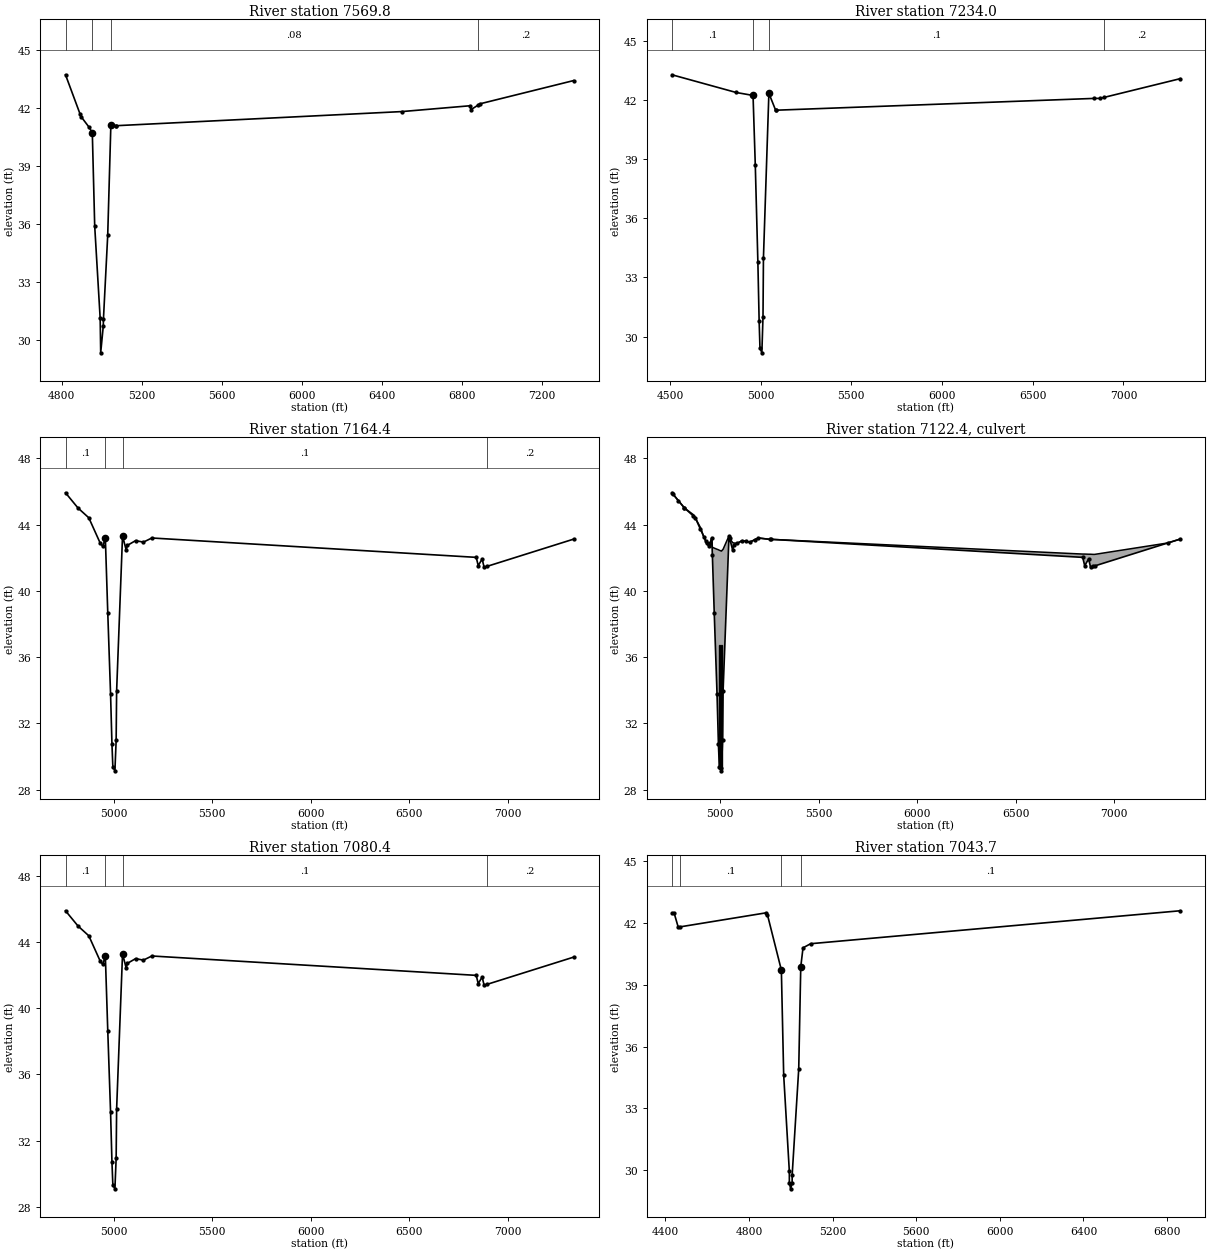
Type RM Length L Ch R = 1 ,7569.8  ,335.7,335.8,467.6
BEGIN DESCRIPTION:
Cross Section 7569.8
END DESCRIPTION:
XS GIS Cut Line= 5
      3134125.06     13793517.38      3134196.35     13793508.59
      3134616.83     13793517.93      3135806.43     13793533.54
      3136663.04      13793577.1
#Sta/Elev= 21
  4818.5    43.7  4890.3    41.7    4897   41.53  4935.7      41  4952.5   40.71
  4964.5   35.88  4991.8   31.12  4994.4   29.34  5007.4   30.73  5008.2   31.09
  5029.5   35.41  5045.2   41.09  5045.3   41.13  5070.8   41.07  5070.9   41.07
  6500.6    41.8  6840.6    42.1  6845.6    41.9  6879.1   42.12  6890.6    42.2
  7358.4    43.4
#Mann= 4 , 1 , 0
  4818.5     .08       0  4952.5     .04       0  5045.2     .08       0
  6879.1      .2       0
Bank Sta=4952.5,5045.2
XS Rating Curve= 0 ,0
Exp/Cntr=0.3,0.1

Type RM Length L Ch R = 1 ,7234.0  ,69.5,69.6,95
BEGIN DESCRIPTION:
Cross Section 7234.0-Interpolated
END DESCRIPTION:
XS GIS Cut Line= 6
      3133809.91     13793827.47      3133903.71     13793830.89
      3134180.99     13793843.22      3134384.33     13793849.38
      3135357.89     13793812.41      3136608.73     13793775.44
#Sta/Elev= 17
  4511.1    43.3    4865    42.4    4958   42.25  4970.4    38.7  4984.6   33.79
  4991.6   30.78  4996.1   29.43  5006.6   29.17  5012.9   31.01  5015.3   33.99
  5045.3   42.36  5082.5    41.5  5085.9    41.5  6840.2    42.1  6870.2    42.1
  6892.7   42.15  7311.6    43.1
#Mann= 4 , 1 , 0
  4511.1      .1       0    4958     .04       0  5045.3      .1       0
  6892.7      .2       0
Bank Sta=4958,5045.3
XS Rating Curve= 0 ,0
Exp/Cntr=0.5,0.3

Type RM Length L Ch R = 1 ,7164.4  ,83.2,84,84.9
BEGIN DESCRIPTION:
Upstream Section of Bridge/Culvert/Weir
END DESCRIPTION:
XS GIS Cut Line= 3
      3134052.62     13793914.82      3134298.08     13793920.33
      3136629.87     13794016.84
#Sta/Elev= 25
  4755.8   45.93  4819.3   45.01  4874.1   44.42    4932   42.89  4945.5   42.69
    4958   43.22  4970.4   38.67  4984.6   33.76  4991.6   30.75  4996.1    29.4
  5006.6   29.14  5012.9   30.98  5015.3   33.96  5045.3   43.33  5064.1   42.46
  5069.3   42.75  5111.6   43.04  5151.1   42.95  5194.3    43.2  6841.1   42.03
  6851.1   41.53  6871.1   41.93  6881.1   41.43  6894.1   41.48  7335.1   43.13
#Mann= 4 , 1 , 0
  4755.8      .1       0    4958    .035       0  5045.3      .1       0
  6894.1      .2       0
#XS Ineff= 2 , 0
       0    4948    42.7    5056       0    42.1
Permanent Ineff=
       F       F
Bank Sta=4958,5045.3
XS Rating Curve= 0 ,0
Exp/Cntr=0.5,0.3

Type RM Length L Ch R = 2 ,7122.4  ,,,
BEGIN DESCRIPTION:
DIRT ROAD
Structure ID: C23-05
END DESCRIPTION:
Bridge Culvert--1,0,-1,-1, 0
Deck Dist Width WeirC Skew NumUp NumDn MinLoCord MaxHiCord MaxSubmerge Is_Ogee
10,64,3,0, 43, 43, , , 0.95, 0, 1,1,,
  4755.8  4761.7  4788.5    4818  4819.3  4864.2  4874.1  4899.9  4917.6  4926.4
    4932  4945.5  4950.7    4958  4960.9  4970.4  4984.6  4991.6  4996.1  5006.6
  5007.1  5012.9  5015.3  5045.3  5048.8  5064.1  5069.3  5088.3  5111.6    5131
  5151.1  5175.5  5194.3  5251.3  5257.5  6841.1  6851.1  6871.1  6881.1  6894.1
  6901.4  7272.9  7335.1
   45.92   45.83   45.44   45.02      45    44.6   44.41   43.83   43.26   43.03
   42.88   42.68    42.9   43.21   42.63   42.58   42.51   42.48   42.45    42.4
    42.4   42.48   42.51   43.32   43.16   42.91   42.89   42.87   43.03   42.99
   42.94   43.08   43.19   43.11   43.11   42.22   42.22   42.21   42.21    42.2
    42.2   42.89   43.12
   45.92   45.83   45.44   45.02      45   44.52   44.41   43.73   43.26   43.03
   42.88   42.68    42.9   43.21   42.15   38.66   33.75   30.74   29.39   29.13
   29.28   30.97   33.95   43.32   43.16   42.45   42.74   42.87   43.03   42.99
   42.94   43.08   43.19   43.11   43.11   42.02   41.52   41.92   41.42   41.47
    41.5   42.89   43.12
  4755.8  4761.7  4788.5    4818  4819.3  4864.2  4874.1  4899.9  4917.6  4926.4
    4932  4945.5  4950.7    4958  4960.9  4970.4  4984.6  4991.6  4996.1  5006.6
  5007.1  5012.9  5015.3  5045.3  5048.8  5064.1  5069.3  5088.3  5111.6    5131
  5151.1  5175.5  5194.3  5251.3  5257.5  6841.1  6851.1  6871.1  6881.1  6894.1
  6901.4  7272.9  7335.1
    45.9   45.82   45.43   45.01   44.99    44.6   44.39   43.83   43.25   43.02
   42.87   42.67   42.89    43.2   42.63   42.58   42.51   42.48   42.45    42.4
    42.4   42.48   42.51   43.31   43.15   42.91   42.89   42.86   43.02   42.98
   42.93   43.07   43.18    43.1    43.1   42.22   42.22   42.21   42.21    42.2
    42.2   42.88    43.1
   45.88   45.79    45.4   44.98   44.96   44.48   44.37   43.69   43.22   42.99
   42.84   42.64   42.86   43.17   42.11   38.62   33.71    30.7   29.35   29.09
   29.24   30.93   33.91   43.28   43.12   42.41    42.7   42.83   42.99   42.95
    42.9   43.04   43.15   43.07   43.07   41.98   41.48   41.88   41.38   41.43
   41.46   42.85   43.08
BR Coef= 1 , 0 , 0 ,1.25, 0 ,,,0.8,-1,2,0,
WSPro=,,,, 1 ,,,, 0 ,,,, 0 ,,,,-1 ,-1 ,-1 , 0 , 0 , 0 , 0 , 0
Culvert=2,7.5,7.5,64,0.015,0.4,1,8,1,29.24,4997.1,29.17,4997.1,Culvert #1  , 0 ,10
Culvert Bottom n=0.015
Culvert=2,7.5,7.5,64,0.015,0.4,1,8,1,29.24,5006.9,29.11,5006.9,Culvert #2  , 0 ,10
Culvert Bottom n=0.015
BR U #Sta/Elev= 43
  4755.8   45.92  4761.7   45.83  4788.5   45.44    4818   45.02  4819.3      45
  4864.2   44.52  4874.1   44.41  4899.9   43.73  4917.6   43.26  4926.4   43.03
    4932   42.88  4945.5   42.68  4950.7    42.9    4958   43.21  4960.9   42.15
  4970.4   38.66  4984.6   33.75  4991.6   30.74  4996.1   29.39  5006.6   29.13
  5007.1   29.28  5012.9   30.97  5015.3   33.95  5045.3   43.32  5048.8   43.16
  5064.1   42.45  5069.3   42.74  5088.3   42.87  5111.6   43.03    5131   42.99
  5151.1   42.94  5175.5   43.08  5194.3   43.19  5251.3   43.11  5257.5   43.11
  6841.1   42.02  6851.1   41.52  6871.1   41.92  6881.1   41.42  6894.1   41.47
  6901.4    41.5  7272.9   42.89  7335.1   43.12
BR U #Mann= 4
  4755.8      .1    4958    .035  5045.3      .1  6894.1      .2
BR U Banks=4958,5045.3
BR D #Sta/Elev= 43
  4755.8   45.88  4761.7   45.79  4788.5    45.4    4818   44.98  4819.3   44.96
  4864.2   44.48  4874.1   44.37  4899.9   43.69  4917.6   43.22  4926.4   42.99
    4932   42.84  4945.5   42.64  4950.7   42.86    4958   43.17  4960.9   42.11
  4970.4   38.62  4984.6   33.71  4991.6    30.7  4996.1   29.35  5006.6   29.09
  5007.1   29.24  5012.9   30.93  5015.3   33.91  5045.3   43.28  5048.8   43.12
  5064.1   42.41  5069.3    42.7  5088.3   42.83  5111.6   42.99    5131   42.95
  5151.1    42.9  5175.5   43.04  5194.3   43.15  5251.3   43.07  5257.5   43.07
  6841.1   41.98  6851.1   41.48  6871.1   41.88  6881.1   41.38  6894.1   41.43
  6901.4   41.46  7272.9   42.85  7335.1   43.08
BR D #Mann= 4
  4755.8      .1    4958    .035  5045.3      .1  6894.1      .2
BR D Banks=4958,5045.3
BC Design=,, 0 ,, 0 ,,,,,,
BC HTab HWMax=45.93
BC Use User HTab Curves=0
BC User HTab FreeFlow(D)= 0

Type RM Length L Ch R = 1 ,7080.4  ,35.4,36.7,37.6
BEGIN DESCRIPTION:
Downstream Section of Bridge/Culvert/Weir
END DESCRIPTION:
XS GIS Cut Line= 3
      3134050.73      13793998.8      3134296.18     13794004.31
      3136627.97     13794100.82
#Sta/Elev= 25
  4755.8   45.88  4819.3   44.96  4874.1   44.37    4932   42.84  4945.5   42.64
    4958   43.17  4970.4   38.62  4984.6   33.71  4991.6    30.7  4996.1   29.35
  5006.6   29.09  5012.9   30.93  5015.3   33.91  5045.3   43.28  5064.1   42.41
  5069.3    42.7  5111.6   42.99  5151.1    42.9  5194.3   43.15  6841.1   41.98
  6851.1   41.48  6871.1   41.88  6881.1   41.38  6894.1   41.43  7335.1   43.08
#Mann= 4 , 1 , 0
  4755.8      .1       0    4958    .035       0  5045.3      .1       0
  6894.1      .2       0
#XS Ineff= 2 , 0
       0    4948    42.7    5056       0    42.2
Permanent Ineff=
       F       F
Bank Sta=4958,5045.3
XS Rating Curve= 0 ,0
Exp/Cntr=0.5,0.3

Type RM Length L Ch R = 1 ,7043.7  ,683.2,682.7,682.2
BEGIN DESCRIPTION:
Cross Section 7043.7-Interpolated
END DESCRIPTION:
XS GIS Cut Line= 5
      3133725.94     13794039.95      3134182.71     13794032.89
      3134389.22     13794040.43      3136045.53     13794068.16
      3136155.48     13794071.16
#Sta/Elev= 18
  4431.8    42.5  4441.8    42.5  4461.8    41.8  4471.4   41.82  4881.8    42.5
  4888.6    42.4    4955   39.72  4966.1   34.62  4993.1   29.95  4993.3   29.37
  4999.5   29.09  5006.5   29.37  5006.8   29.78  5038.1   34.92  5047.8   39.88
  5058.6    40.8  5095.2      41  6861.8    42.6
#Mann= 4 , 1 , 0
  4431.8    .012       0  4471.4      .1       0    4955     .04       0
  5047.8      .1       0
Bank Sta=4955,5047.8
XS Rating Curve= 0 ,0
Exp/Cntr=0.3,0.1

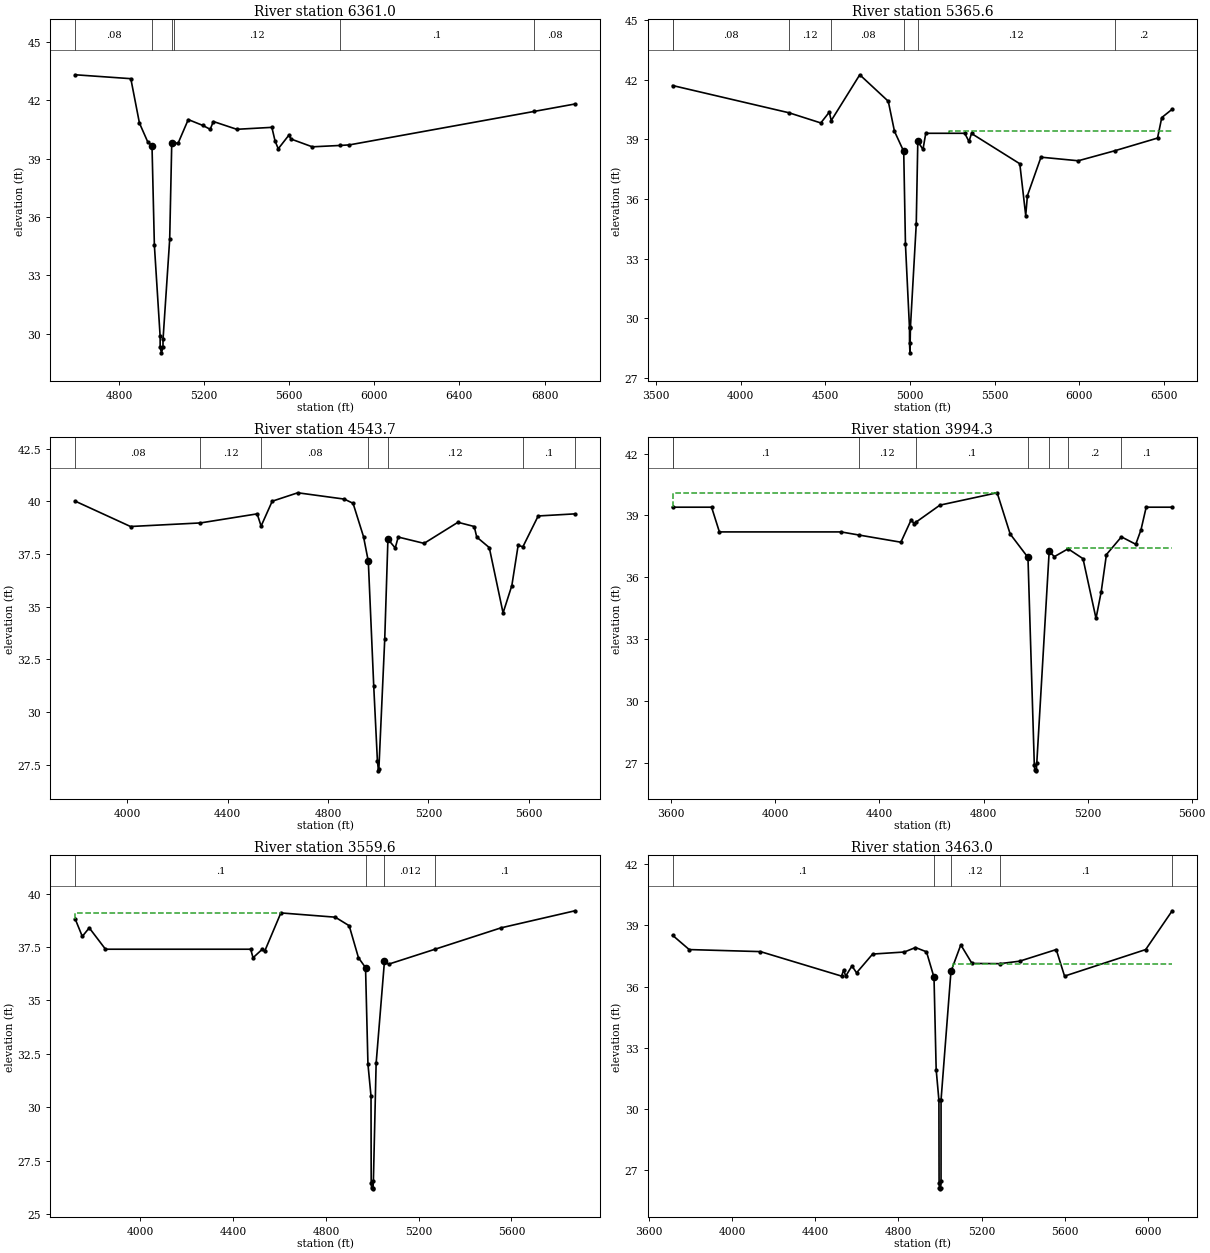
Type RM Length L Ch R = 1 ,6361.0  ,996.1,995.4,993.7
BEGIN DESCRIPTION:
Cross Section 6361.0
END DESCRIPTION:
XS GIS Cut Line= 5
       3133866.8     13794708.62      3134062.58     13794713.74
      3134465.42     13794724.34      3135147.42     13794621.86
      3136139.67     13794248.93
#Sta/Elev= 30
  4594.6    43.3  4855.4    43.1  4895.9   40.82  4934.6   39.86    4955   39.65
  4966.1   34.55  4993.1   29.88  4993.3    29.3  4999.5   29.02  5006.5    29.3
  5006.8   29.71  5038.1   34.85  5047.8   39.81    5059    39.8  5077.4   39.78
  5125.4      41  5193.4    40.7  5228.4    40.5  5243.4    40.9  5353.4    40.5
  5518.4    40.6  5533.4    39.9  5548.4    39.5  5598.4    40.2  5608.4      40
  5708.4    39.6  5837.8   39.67  5883.1    39.7  6752.2   41.42  6943.1    41.8
#Mann= 6 , 1 , 0
  4594.6     .08       0    4955     .04       0  5047.8     .08       0
    5059     .12       0  5837.8      .1       0  6752.2     .08       0
#XS Ineff= 2 , 0
       0                  5243.4       0    40.9
Permanent Ineff=
       F       F
Bank Sta=4955,5047.8
XS Rating Curve= 0 ,0
Exp/Cntr=0.3,0.1

Type RM Length L Ch R = 1 ,5365.6  ,821.8,821.9,855.4
BEGIN DESCRIPTION:
Cross Section 5365.6
END DESCRIPTION:
XS GIS Cut Line= 6
      3132854.06     13795540.62      3133960.16     13795705.61
      3134126.19     13795713.77      3134391.21     13795713.77
      3135437.78     13795597.88      3135776.34     13795523.31
#Sta/Elev= 30
  3598.6    41.7  4286.3   40.33  4473.6   39.82  4523.6   40.36  4535.3   39.94
  4703.6   42.24  4871.9   40.91  4908.5    39.4  4963.1   38.39  4973.3   33.72
  4997.2    29.5  4997.4   28.75  4999.8   28.27  5002.8   29.57    5037   34.73
  5046.2   38.89  5076.7   38.49  5093.2    39.3  5323.2    39.3  5348.2   38.89
  5363.2   39.29  5648.2   37.77  5683.2   35.17  5693.2   36.17  5773.2    38.1
  5993.2   37.92  6207.7   38.42  6461.2   39.06  6486.2   40.09  6547.8   40.51
#Mann= 7 , 1 , 0
  3598.6      .2       0  3598.6     .08       0  4286.3     .12       0
  4535.3     .08       0  4963.1    .035       0  5046.2     .12       0
  6207.7      .2       0
#XS Ineff= 2 , 0
       0                  5228.2       0   39.42
Permanent Ineff=
       F       F
Bank Sta=4963.1,5046.2
XS Rating Curve= 0 ,0
Exp/Cntr=0.3,0.1

Type RM Length L Ch R = 1 ,4543.7  ,548.2,549.4,573.4
BEGIN DESCRIPTION:
Cross Section 4543.7
END DESCRIPTION:
XS GIS Cut Line= 5
      3133047.46     13796241.94      3133892.71     13796510.94
      3134076.71     13796533.59      3134394.75     13796537.12
      3134995.47     13796501.78
#Sta/Elev= 30
  3792.3      40  4012.3    38.8  4291.3   38.97  4517.3    39.4    4533   38.82
  4577.3      40  4679.3    40.4  4864.7    40.1  4899.7    39.9  4941.3   38.32
  4960.5   37.15  4982.1   31.23  4996.8   27.67    5001   27.21  5002.6    27.3
    5026   33.47  5038.7    38.2  5067.8   37.78  5079.7    38.3  5182.8      38
  5317.8      39  5382.8    38.8  5392.8    38.3  5442.8    37.8  5497.8    34.7
  5532.8      36  5557.8    37.9  5576.9   37.84  5637.8    39.3  5784.5    39.4
#Mann= 7 , 1 , 0
  3792.3     .08       0  4291.3     .12       0    4533     .08       0
  4960.5    .035       0  5038.7     .12       0  5576.9      .1       0
  5784.5      .2       0
#XS Ineff= 2 , 0
       0                  5317.8       0      39
Permanent Ineff=
       F       F
Bank Sta=4960.5,5038.7
XS Rating Curve= 0 ,0
Exp/Cntr=0.3,0.1

Type RM Length L Ch R = 1 ,3994.3  ,434.6,434.7,438.1
BEGIN DESCRIPTION:
Cross Section 3994.3-Interpolated
END DESCRIPTION:
XS GIS Cut Line= 4
      3132829.81     13796856.33      3133446.35      13797054.5
      3134558.32     13797098.54      3134714.77     13797065.16
#Sta/Elev= 30
  3604.8    39.4  3754.8    39.4  3784.8    38.2  4252.4    38.2  4320.7   38.05
  4482.4    37.7  4522.4    38.8  4532.4    38.6  4538.9   38.66  4632.4    39.5
  4852.4    40.1  4902.4    38.1 4970.85   36.96 4995.25   26.88 4997.05   26.64
 5001.65    26.6 5003.15   26.66 5004.75   26.98 5052.35   37.25  5072.4      37
    5125   37.38  5182.4    36.9  5232.4      34  5252.4    35.3  5272.4    37.1
    5330   37.96  5385.2    37.6  5405.2    38.3  5425.2    39.4  5525.2    39.4
#Mann= 8 , 1 , 0
  3604.8      .2       0  3604.8      .1       0  4320.7     .12       0
  4538.9      .1       0 4970.85    .045       0 5052.35     .12       0
    5125      .2       0    5330      .1       0
#XS Ineff= 2 , 0
       0  4852.4    40.1  5122.4       0    37.4
Permanent Ineff=
       F       F
Bank Sta=4970.85,5052.35
XS Rating Curve= 0 ,0
Exp/Cntr=0.3,0.1

Type RM Length L Ch R = 1 ,3559.6  ,95.2,96.65,103
BEGIN DESCRIPTION:
Cross Section 3559.6-Interpolated
END DESCRIPTION:
XS GIS Cut Line= 6
      3132895.58     13797444.65      3133579.96     13797490.01
       3134013.6     13797517.93      3134317.77     13797517.93
      3135006.75     13797526.86      3135046.71     13797527.66
#Sta/Elev= 26
    3720    38.8    3750      38    3780    38.4    3850    37.4  4475.9    37.4
  4485.9      37  4525.9    37.4  4535.9    37.3  4605.9    39.1  4840.4    38.9
  4900.4    38.5  4940.4      37 4970.85   36.54 4981.25   32.02 4994.45   30.52
 4995.25   26.46 4997.05   26.22 5001.65   26.18 5003.15   26.24 5004.75   26.56
 5016.55   32.06 5052.35   36.83  5070.4    36.7  5270.4    37.4  5554.6    38.4
  5873.6    39.2
#Mann= 4 , 1 , 0
    3720      .1       0 4970.85     .04       0 5052.35    .012       0
  5270.4      .1       0
#XS Ineff= 2 , 0
       0  4605.9    39.1               0
Permanent Ineff=
       F       F
Bank Sta=4970.85,5052.35
XS Rating Curve= 0 ,0
Exp/Cntr=0.5,0.3

Type RM Length L Ch R = 1 ,3463.0  ,77.5,77.5,77.5
BEGIN DESCRIPTION:
Upstream Section of Bridge/Culvert/Weir
END DESCRIPTION:
XS GIS Cut Line= 6
      3132874.14     13797532.24      3133430.65      13797597.3
      3133682.79      13797606.1      3134046.76     13797609.63
      3134559.14     13797620.23      3135271.81     13797639.57
#Sta/Elev= 30
    3714   38.51    3794   37.81  4136.5   37.71  4526.5   36.51  4536.5   36.81
  4546.5   36.51  4576.5   37.01  4598.5   36.67  4675.8   37.59  4828.1   37.69
  4881.9   37.91  4934.8    37.7  4970.9   36.45  4981.3   31.93  4994.5   30.43
  4995.3   26.37  4997.1   26.13  5001.7   26.09  5003.2   26.15  5004.7   26.47
  5004.8   30.45  5052.4   36.74  5099.7   38.04  5153.6   37.13  5287.2   37.12
  5382.1   37.24  5558.5   37.81  5598.5   36.51  5988.5   37.81    6116   39.71
#Mann= 5 , 1 , 0
    3714      .1       0  4970.9     .04       0  5052.4     .12       0
  5287.2      .1       0    6116      .2       0
#XS Ineff= 2 , 0
       0    4935      37    5061       0   37.11
Permanent Ineff=
       F       F
Bank Sta=4970.9,5052.4
XS Rating Curve= 0 ,0
Exp/Cntr=0.5,0.3

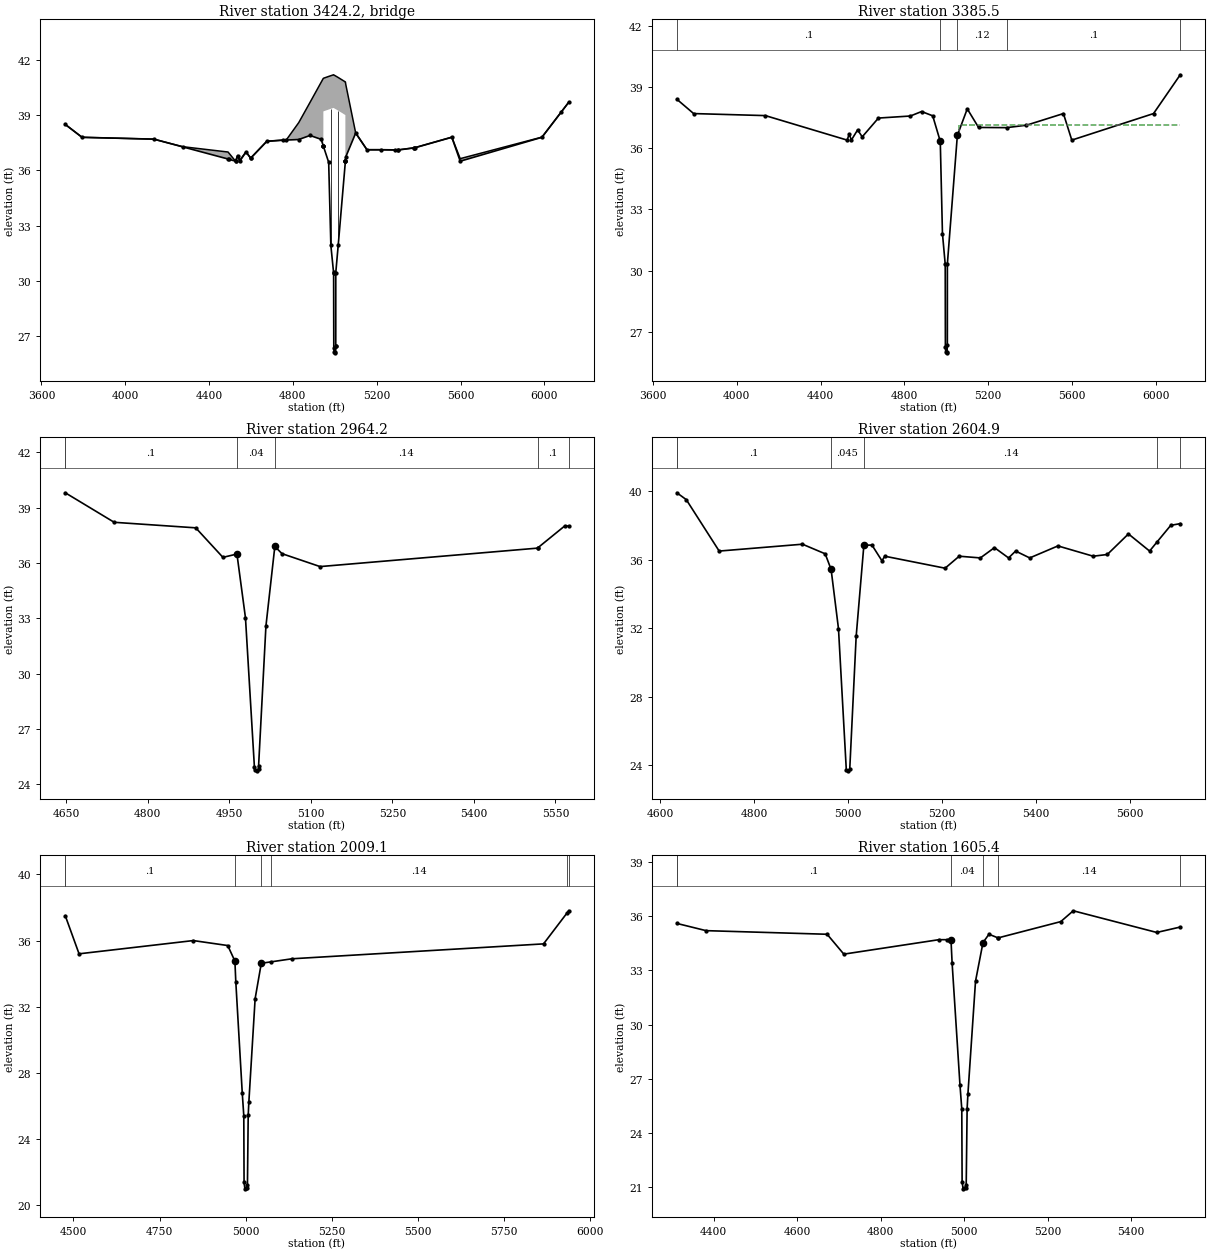
Type RM Length L Ch R = 3 ,3424.2  ,,,
BEGIN DESCRIPTION:
SELINSKY ROAD
Structure ID: C23-4
END DESCRIPTION:
Bridge Culvert--1,0,-1,-1, 0
Deck Dist Width WeirC Skew NumUp NumDn MinLoCord MaxHiCord MaxSubmerge Is_Ogee
10,57.5,2.6,0, 55, 55, , , 0.95, 0, 1,1,,
    3714    3794  4136.5  4274.3  4490.7  4496.5  4526.5  4526.6  4536.5  4546.5
  4576.5  4598.4  4598.5  4675.8  4751.7  4768.9  4828.1  4881.9  4934.8 4945.51
  4945.6  4945.7  4945.8  4970.9  4981.3  4994.2  4994.4  4994.5  4995.3  4997.1
  5001.7  5003.2  5004.6  5004.7  5004.8  5016.6 5050.59  5050.7  5050.8  5050.9
  5052.4  5099.7  5153.6  5222.3  5287.2    5301  5303.2  5377.6  5377.7  5382.1
  5558.5  5598.5  5988.5  6080.6    6116
    38.5    37.8    37.7   37.29      37   36.92    36.5    36.5   36.81   36.55
   37.01   36.67   36.67   37.59   37.65   37.66    38.6    39.7   40.79   41.01
   41.01   41.01   41.01   41.11   41.15    41.2    41.2    41.2   41.19   41.18
   41.15   41.14   41.13   41.13   41.13   41.05   40.81   40.81   40.81    40.8
   40.68   38.04   37.13   37.13   37.12   37.12   37.12   37.23   37.23   37.24
   37.81   36.64   37.81   39.18    39.7
    38.5    37.8    37.7   37.28   36.62    36.6    36.5    36.5    36.8    36.5
      37   36.67   36.66   37.58   37.64   37.65   37.68    37.9   37.69   37.32
   39.21   39.21   39.21   39.31   39.35    39.4    39.4    39.4   39.39   39.38
   39.35   39.34   39.33   39.33   39.33   39.25   39.01    36.5   36.52   36.53
   36.73   38.03   37.12   37.12   37.11   37.11   37.11   37.22   37.22   37.23
    37.8    36.5    37.8   39.17    39.7
    3714    3794  4136.5  4274.3  4490.7  4496.5  4526.5  4526.6  4536.5  4546.5
  4576.5  4598.4  4598.5  4675.8  4751.7  4768.9  4828.1  4881.9  4934.8 4945.51
  4945.6  4945.7  4945.8  4970.9  4981.3  4994.2  4994.4  4994.5  4995.3  4997.1
  5001.7  5003.2  5004.6  5004.7  5004.8  5016.6 5050.59  5050.7  5050.8  5050.9
  5052.4  5099.7  5153.6  5222.3  5287.2    5301  5303.2  5377.6  5377.7  5382.1
  5558.5  5598.5  5988.5  6080.6    6116
    38.5    37.8    37.7   37.29      37   36.92    36.5    36.5   36.81   36.55
   37.01   36.67   36.67   37.59   37.65   37.66    38.6    39.7   40.79   41.01
   41.01   41.01   41.01   41.11   41.15    41.2    41.2    41.2   41.19   41.18
   41.15   41.14   41.13   41.13   41.13   41.05   40.81   40.81   40.81    40.8
   40.68   38.04   37.13   37.13   37.12   37.12   37.12   37.23   37.23   37.24
   37.81   36.64   37.81   39.18    39.7
   38.42   37.72   37.62    37.2   36.54   36.52   36.42   36.42   36.72   36.42
   36.92   36.59   36.58    37.5   37.56   37.57    37.6   37.82   37.61   37.24
   39.13   39.13   39.13   39.23   39.27   39.32   39.32   39.32   39.31    39.3
   39.27   39.26   39.25   39.25   39.25   39.17   38.93   36.42   36.44   36.45
   36.65   37.95   37.04   37.04   37.03   37.03   37.03   37.14   37.14   37.15
   37.72   36.42   37.72   39.09   39.62
Pier Skew, UpSta & Num, DnSta & Num=  ,4981.2, 2 ,4981.2, 2 , 0 , 0 , 0 ,,
     1.5     1.5
   30.85   40.35
     1.5     1.5
   30.77   40.27
Pier Skew, UpSta & Num, DnSta & Num=  ,5016.5, 2 ,5016.5, 2 , 0 , 0 , 0 ,,
     1.5     1.5
   30.85   40.26
     1.5     1.5
   30.77   40.18
Abutment Skew #Up #Dn= , 2 , 2
  4945.4  4994.4
   39.21   30.43
  4945.4  4994.4
   39.13   30.35
Abutment Skew #Up #Dn= , 2 , 2
  5004.6 5050.79
   26.44   39.01
  5004.6 5050.79
   26.36   38.93
BR Coef= 1 , 1 , 0 ,1.25, 0 ,,,0.8,0,2,0,
WSPro=,,,, 1 ,,,, 0 ,,,, 0 ,,,,-1 ,-1 ,-1 , 0 , 0 , 0 , 0 , 0
BR U #Sta/Elev= 55
    3714    38.5    3794    37.8  4136.5    37.7  4274.3   37.28  4490.7   36.62
  4496.5    36.6  4526.5    36.5  4526.6    36.5  4536.5    36.8  4546.5    36.5
  4576.5      37  4598.4   36.67  4598.5   36.66  4675.8   37.58  4751.7   37.64
  4768.9   37.65  4828.1   37.68  4881.9    37.9  4934.8   37.69 4945.51   37.32
  4945.6   37.32  4945.7   37.31  4945.8   37.31  4970.9   36.44  4981.3   31.92
  4994.2   30.45  4994.4   30.43  4994.5   30.42  4995.3   26.36  4997.1   26.12
  5001.7   26.08  5003.2   26.14  5004.6   26.44  5004.7   26.46  5004.8   30.44
  5016.6   31.96 5050.59   36.49  5050.7    36.5  5050.8   36.52  5050.9   36.53
  5052.4   36.73  5099.7   38.03  5153.6   37.12  5222.3   37.12  5287.2   37.11
    5301   37.11  5303.2   37.11  5377.6   37.22  5377.7   37.22  5382.1   37.23
  5558.5    37.8  5598.5    36.5  5988.5    37.8  6080.6   39.17    6116    39.7
BR U #Mann= 5
    3714      .1  4970.9     .04  5052.4     .12  5287.2      .1    6116      .2
BR U Banks=4970.9,5052.4
BR D #Sta/Elev= 55
    3714   38.42    3794   37.72  4136.5   37.62  4274.3    37.2  4490.7   36.54
  4496.5   36.52  4526.5   36.42  4526.6   36.42  4536.5   36.72  4546.5   36.42
  4576.5   36.92  4598.4   36.59  4598.5   36.58  4675.8    37.5  4751.7   37.56
  4768.9   37.57  4828.1    37.6  4881.9   37.82  4934.8   37.61 4945.51   37.24
  4945.6   37.24  4945.7   37.23  4945.8   37.23  4970.9   36.36  4981.3   31.84
  4994.2   30.37  4994.4   30.35  4994.5   30.34  4995.3   26.28  4997.1   26.04
  5001.7      26  5003.2   26.06  5004.6   26.36  5004.7   26.38  5004.8   30.36
  5016.6   31.88 5050.59   36.41  5050.7   36.42  5050.8   36.44  5050.9   36.45
  5052.4   36.65  5099.7   37.95  5153.6   37.04  5222.3   37.04  5287.2   37.03
    5301   37.03  5303.2   37.03  5377.6   37.14  5377.7   37.14  5382.1   37.15
  5558.5   37.72  5598.5   36.42  5988.5   37.72  6080.6   39.09    6116   39.62
BR D #Mann= 5
    3714      .1  4970.9     .04  5052.4     .12  5287.2      .1    6116      .2
BR D Banks=4970.9,5052.4
BC Design=,, 0 ,, 0 ,,,,,,
BC HTab HWMax=39.71
BC Use User HTab Curves=0
BC User HTab FreeFlow(D)= 0

Type RM Length L Ch R = 1 ,3385.5  ,421.25,421.25,421.25
BEGIN DESCRIPTION:
Downstream Section of Bridge/Culvert/Weir
END DESCRIPTION:
XS GIS Cut Line= 6
      3132842.19     13797602.85      3133398.69      13797667.9
      3133650.83      13797676.7       3134014.8     13797680.23
      3134527.18     13797690.83      3135239.86     13797710.18
#Sta/Elev= 30
    3714   38.39    3794   37.69  4136.5   37.59  4526.5   36.39  4536.5   36.69
  4546.5   36.39  4576.5   36.89  4598.5   36.55  4675.8   37.47  4828.1   37.57
  4881.9   37.79  4934.8   37.58  4970.9   36.33  4981.3   31.81  4994.5   30.31
  4995.3   26.25  4997.1   26.01  5001.7   25.97  5003.2   26.03  5004.7   26.35
  5004.8   30.33  5052.4   36.62  5099.7   37.92  5153.6   37.01  5287.2      37
  5382.1   37.12  5558.5   37.69  5598.5   36.39  5988.5   37.69    6116   39.59
#Mann= 5 , 1 , 0
    3714      .1       0  4970.9     .04       0  5052.4     .12       0
  5287.2      .1       0    6116      .2       0
#XS Ineff= 2 , 0
       0    4935      37    5061       0   37.11
Permanent Ineff=
       F       F
Bank Sta=4970.9,5052.4
XS Rating Curve= 0 ,0
Exp/Cntr=0.5,0.3

Type RM Length L Ch R = 1 ,2964.2  ,358.4,359.3,360.6
BEGIN DESCRIPTION:
Cross Section 2964.2-Interpolated
END DESCRIPTION:
XS GIS Cut Line= 4
      3133595.29     13797968.53      3133894.95     13798042.15
      3133968.29     13798074.51      3134467.61     13798272.83
#Sta/Elev= 19
  4648.3    39.8  4738.3    38.2  4888.3    37.9  4938.3    36.3  4964.1   36.48
  4979.8   33.02  4996.2   24.95  4996.4    24.8  5000.3   24.73  5003.8   24.85
  5003.9   24.98  5017.4   32.57  5033.8   36.89    5047    36.5    5117    35.8
    5517    36.8  5517.3   36.81    5567      38  5574.3      38
#Mann= 6 , 1 , 0
  4648.3      .2       0  4648.3      .1       0  4964.1     .04       0
  5033.8     .14       0  5517.3      .1       0  5574.3      .2       0
Bank Sta=4964.1,5033.8
XS Rating Curve= 0 ,0
Exp/Cntr=0.3,0.1

Type RM Length L Ch R = 1 ,2604.9  ,593.4,595.8,596.7
BEGIN DESCRIPTION:
Cross Section 2604.9
END DESCRIPTION:
XS GIS Cut Line= 4
      3133433.58     13798245.66      3133684.48     13798337.54
      3133903.56     13798443.55      3134461.89     13798489.48
#Sta/Elev= 30
    4636    39.9    4656    39.5    4726    36.5  4903.2    36.9  4951.5   36.34
  4964.1   35.43  4979.8   31.97  4996.4   23.75  5000.3   23.68  5003.8    23.8
  5017.4   31.52  5033.8   36.84    5051   36.85  5072.3   35.93  5078.2    36.2
  5206.6    35.5  5236.6    36.2  5281.6    36.1  5311.6    36.7  5341.6    36.1
  5356.6    36.5  5386.6    36.1  5446.6    36.8  5521.6    36.2  5551.6    36.3
  5596.6    37.5  5641.6    36.5    5658   37.05  5686.6      38  5706.8    38.1
#Mann= 6 , 1 , 0
    4636      .2       0    4636      .1       0  4964.1    .045       0
  5033.8     .14       0    5658      .1       0  5706.8      .2       0
Bank Sta=4964.1,5033.8
XS Rating Curve= 0 ,0
Exp/Cntr=0.3,0.1

Type RM Length L Ch R = 1 ,2009.1  ,418,403.7,391.7
BEGIN DESCRIPTION:
Cross Section 2009.1-Interpolated
END DESCRIPTION:
XS GIS Cut Line= 4
      3132994.13     13798766.43      3133359.41     13798834.07
      3133611.94     13798969.36      3134414.64     13798951.32
#Sta/Elev= 22
  4476.2    37.5  4516.2    35.2  4847.7      36  4947.7    35.7  4968.5   34.76
  4971.1   33.51  4989.9   26.77  4994.3   25.42  4995.1   21.39  4997.5      21
  5000.6   21.07  5003.8   21.04  5004.9   21.21  5007.1   25.44    5009   26.25
  5027.2   32.49  5045.1   34.63  5072.2   34.71  5134.2    34.9  5864.2    35.8
  5932.9   37.68  5937.1    37.8
#Mann= 7 , 1 , 0
  4476.2      .2       0  4476.2      .1       0  4968.5    .045       0
  5045.1      .1       0  5072.2     .14       0  5932.9      .1       0
  5937.1      .2       0
Bank Sta=4968.5,5045.1
XS Rating Curve= 0 ,0
Exp/Cntr=0.3,0.1

Type RM Length L Ch R = 1 ,1605.4  ,22,22.5,27
BEGIN DESCRIPTION:
Cross Section 1605.4-Interpolated
END DESCRIPTION:
XS GIS Cut Line= 4
       3132614.5     13799233.21      3133241.86     13799253.64
       3133382.8     13799271.26      3133819.05     13799267.79
#Sta/Elev= 26
  4311.7    35.6  4381.7    35.2  4671.7      35  4711.7    33.9  4939.4    34.7
  4959.4    34.7  4968.5   34.67  4971.1   33.42  4989.9   26.68  4994.3   25.33
  4995.1    21.3  4997.5   20.91  5000.6   20.98  5003.8   20.95  5004.9   21.12
  5007.1   25.35    5009   26.16  5027.2    32.4  5045.1   34.54  5059.4      35
  5081.2    34.8  5081.4    34.8  5231.4    35.7  5261.4    36.3  5461.4    35.1
  5517.7    35.4
#Mann= 6 , 1 , 0
  4311.7      .2       0  4311.7      .1       0  4968.5     .04       0
  5045.1      .1       0  5081.2     .14       0  5517.7      .2       0
Bank Sta=4968.5,5045.1
XS Rating Curve= 0 ,0
Exp/Cntr=0.5,0.3