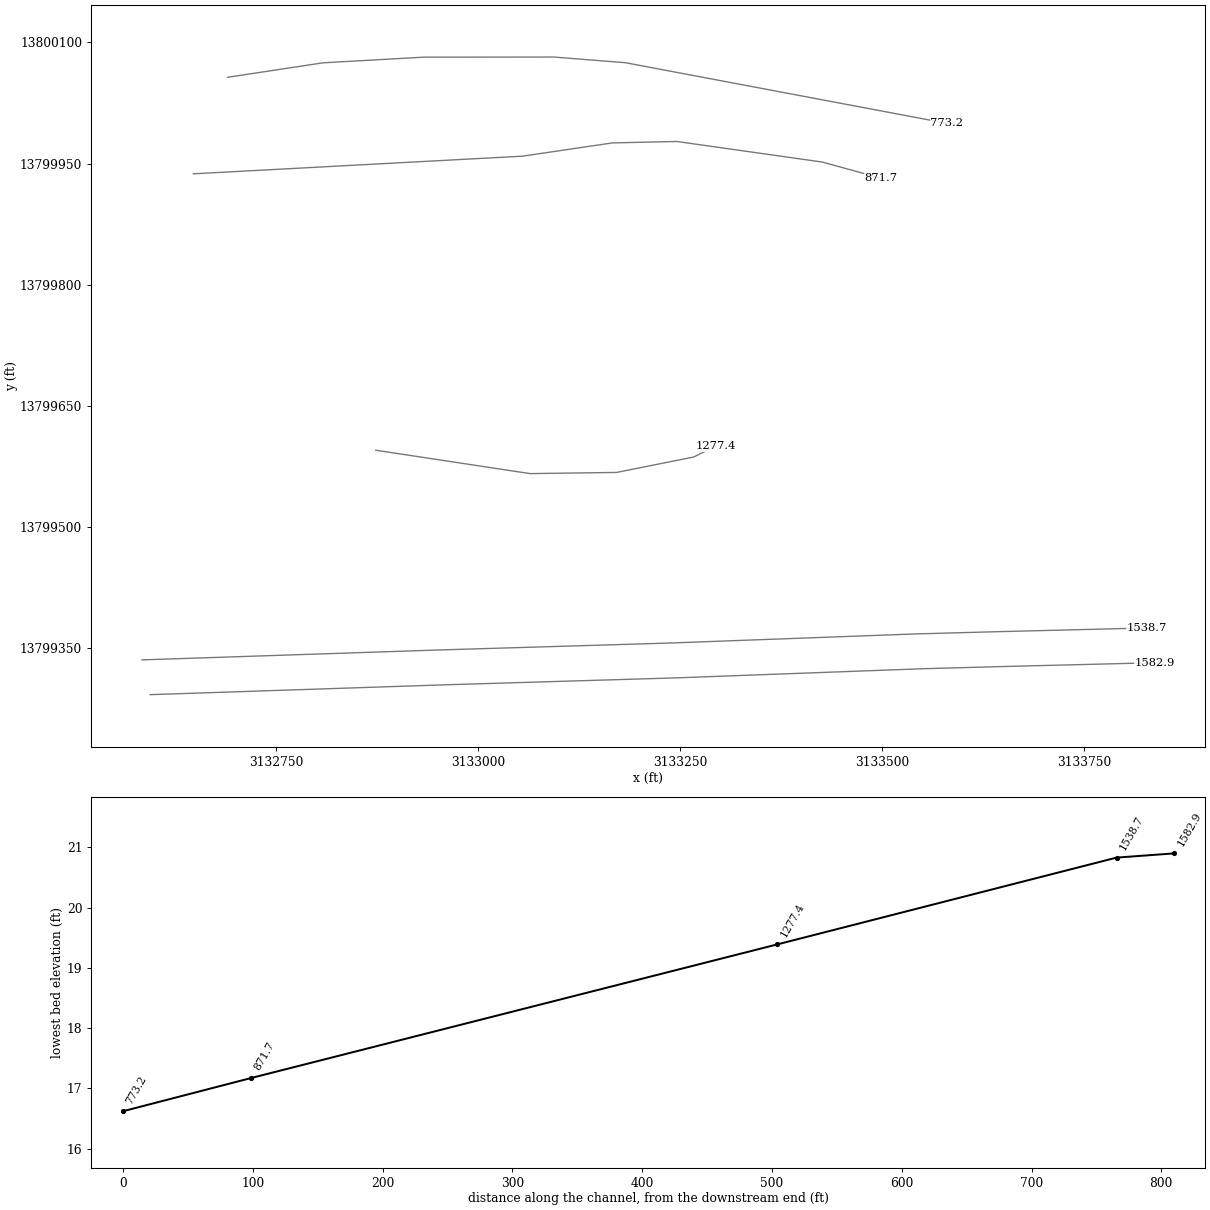
HEC-RAS study C123-00-00.PRJ: C123-00-00

--- C123-00-00.g02 (geometry) --- (continued)

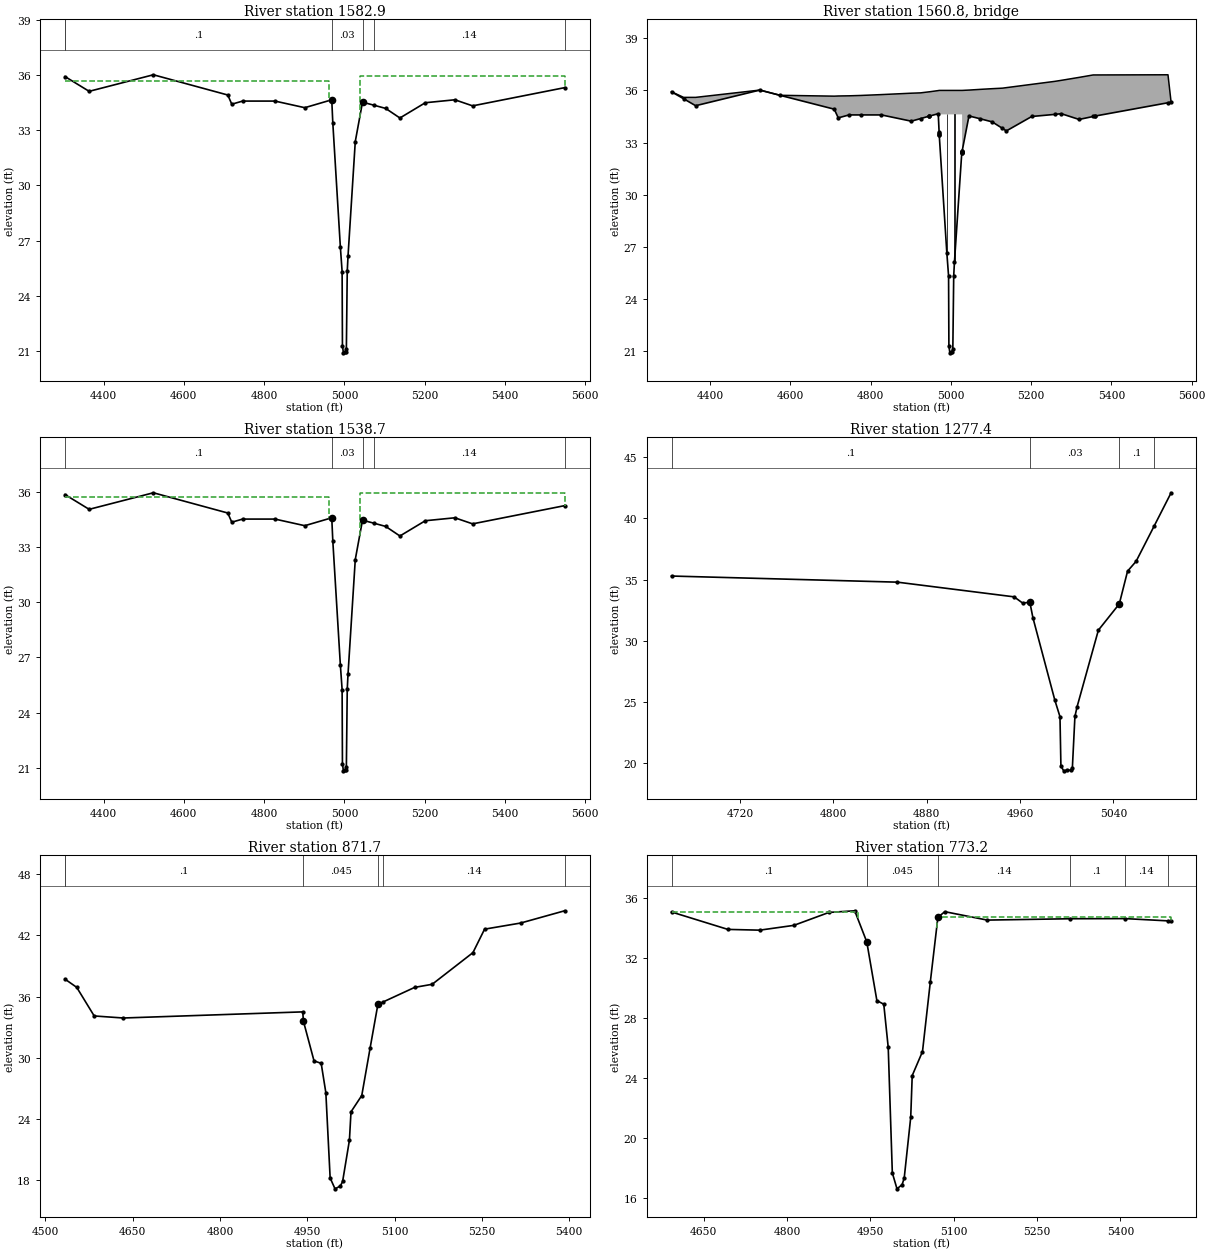
Type RM Length L Ch R = 1 ,1582.9  ,44.8,44.2,43.9
BEGIN DESCRIPTION:
Upstream Section of Bridge/Culvert/Weir
END DESCRIPTION:
XS GIS Cut Line= 6
      3132593.68     13799292.79      3132962.98      13799305.1
      3133245.67     13799313.58      3133550.98     13799324.88
      3133647.18     13799327.53      3133837.84      13799332.3
#Sta/Elev= 28
    4304   35.92    4364   35.12    4524   36.02  4709.4   34.92  4719.4   34.42
  4746.4   34.59    4827   34.59  4901.3   34.23  4968.5   34.66  4971.1   33.41
  4989.9   26.67  4994.3   25.32  4995.1   21.29  4997.5    20.9  5000.6   20.97
  5003.8   20.94  5004.9   21.11  5007.1   25.34    5009   26.15  5027.1   32.39
  5045.1   34.53  5072.9   34.37  5102.9   34.19  5138.3   33.67  5201.6    34.5
  5275.2   34.66  5319.5   34.33  5548.8   35.32
#Mann= 6 , 1 , 0
    4304      .2       0    4304      .1       0  4968.5     .03       0
  5045.1      .1       0  5072.9     .14       0  5548.8      .2       0
#XS Ineff= 2 , 0
       0    4961    35.7    5038       0   35.95
Permanent Ineff=
       F       F
Bank Sta=4968.5,5045.1
XS Rating Curve= 0 ,0
Exp/Cntr=0.5,0.3

Type RM Length L Ch R = 3 ,1560.8  ,,,
BEGIN DESCRIPTION:
SOUTH ACRES
Structure ID: C23-3
END DESCRIPTION:
Bridge Culvert--1,0,-1,-1, 0
Deck Dist Width WeirC Skew NumUp NumDn MinLoCord MaxHiCord MaxSubmerge Is_Ogee
10,24.2,2.6,0, 52, 52, , , 0.95, 0, 1,1,,
    4304  4334.1    4364    4524  4574.1  4709.4  4719.4  4746.4  4775.4    4827
  4901.3  4924.7 4945.99  4946.1 4946.21  4968.5  4970.7 4970.81  4970.9    4971
  4971.1  4989.9  4994.3  4995.1  4997.5  5000.6  5003.8  5004.9  5007.1    5009
  5027.1  5027.2 5027.59  5027.7 5027.81 5027.89    5028  5028.1  5045.1  5072.9
  5102.9  5128.3  5138.3  5201.6  5258.6  5275.2  5319.5  5354.6  5358.2  5358.3
    5541  5548.8
   35.92    35.6    35.6   36.02   35.72   35.67   35.68   35.69   35.71   35.76
   35.84   35.86   35.92   35.92   35.92   35.99      36      36      36      36
      36      36      36      36      36      36      36      36      36      36
      36      36      36      36      36      36      36      36   36.02   36.06
    36.1   36.13   36.16   36.35   36.52   36.58   36.75   36.89   36.89   36.89
    36.9   35.32
   35.92   35.52   35.12   36.02   35.72   34.92   34.42   34.59   34.59   34.59
   34.23   34.38   34.52   34.52   34.52   34.66    33.6   33.55   34.62   34.62
   34.62   34.62   34.62   34.62   34.62   34.62   34.62   34.62   34.62   34.62
   34.62   34.62   34.62   34.62   34.62   34.62    32.5   32.51   34.53   34.37
   34.19   33.82   33.67    34.5   34.62   34.66   34.33    34.5   34.52   34.52
   35.29   35.32
    4304  4334.1    4364    4524  4574.1  4709.4  4719.4  4746.4  4775.4    4827
  4901.3  4924.7 4945.99  4946.1 4946.21  4968.5  4970.7 4970.81  4970.9    4971
  4971.1  4989.9  4994.3  4995.1  4997.5  5000.6  5003.8  5004.9  5007.1    5009
  5027.1  5027.2 5027.59  5027.7 5027.81 5027.89    5028  5028.1  5045.1  5072.9
  5102.9  5128.3  5138.3  5201.6  5258.6  5275.2  5319.5  5354.6  5358.2  5358.3
    5541  5548.8
    35.9    35.6    35.6   36.01   35.71   35.67   35.68   35.69   35.71   35.76
   35.84   35.86   35.92   35.92   35.92   35.99      36      36      36      36
      36      36      36      36      36      36      36      36      36      36
      36      36      36      36      36      36      36      36   36.02   36.06
    36.1   36.13   36.16   36.35   36.52   36.58   36.75   36.89   36.89   36.89
    36.9    35.3
    35.9    35.5    35.1      36    35.7    34.9    34.4   34.57   34.57   34.57
   34.21   34.36    34.5    34.5    34.5   34.64   33.58   33.53    34.6    34.6
    34.6    34.6    34.6    34.6    34.6    34.6    34.6    34.6    34.6    34.6
    34.6    34.6    34.6    34.6    34.6    34.6   32.48   32.49   34.51   34.35
   34.17    33.8   33.65   34.48    34.6   34.64   34.31   34.48    34.5    34.5
   35.27    35.3
Pier Skew, UpSta & Num, DnSta & Num=  ,4989.9, 2 ,4989.9, 2 , 0 , 0 , 0 ,,
     1.2     1.2
   25.49   35.62
     1.2     1.2
   25.47    35.6
Pier Skew, UpSta & Num, DnSta & Num=  ,5009, 2 ,5009, 2 , 0 , 0 , 0 ,,
     1.2     1.2
   24.89   35.62
     1.2     1.2
   24.87    35.6
BR Coef= 1 , 1 , 0 ,1.25, 0 ,,,0.8,0,2,0,
WSPro=,,,, 1 ,,,, 0 ,,,, 0 ,,,,-1 ,-1 ,-1 , 0 , 0 , 0 , 0 , 0
BR U #Sta/Elev= 52
    4304   35.92  4334.1   35.52    4364   35.12    4524   36.02  4574.1   35.72
  4709.4   34.92  4719.4   34.42  4746.4   34.59  4775.4   34.59    4827   34.59
  4901.3   34.23  4924.7   34.38 4945.99   34.52  4946.1   34.52 4946.21   34.52
  4968.5   34.66  4970.7    33.6 4970.81   33.55  4970.9   33.51    4971   33.46
  4971.1   33.41  4989.9   26.67  4994.3   25.32  4995.1   21.29  4997.5    20.9
  5000.6   20.97  5003.8   20.94  5004.9   21.11  5007.1   25.34    5009   26.15
  5027.1   32.39  5027.2    32.4 5027.59   32.45  5027.7   32.46 5027.81   32.47
 5027.89   32.48    5028    32.5  5028.1   32.51  5045.1   34.53  5072.9   34.37
  5102.9   34.19  5128.3   33.82  5138.3   33.67  5201.6    34.5  5258.6   34.62
  5275.2   34.66  5319.5   34.33  5354.6    34.5  5358.2   34.52  5358.3   34.52
    5541   35.29  5548.8   35.32
BR U #Mann= 5
    4304      .1  4968.5    .035  5045.1      .1  5072.9     .14  5548.8      .2
BR U Banks=4968.5,5045.1
BR D #Sta/Elev= 52
    4304    35.9  4334.1    35.5    4364    35.1    4524      36  4574.1    35.7
  4709.4    34.9  4719.4    34.4  4746.4   34.57  4775.4   34.57    4827   34.57
  4901.3   34.21  4924.7   34.36 4945.99    34.5  4946.1    34.5 4946.21    34.5
  4968.5   34.64  4970.7   33.58 4970.81   33.53  4970.9   33.49    4971   33.44
  4971.1   33.39  4989.9   26.65  4994.3    25.3  4995.1   21.27  4997.5   20.88
  5000.6   20.95  5003.8   20.92  5004.9   21.09  5007.1   25.32    5009   26.13
  5027.1   32.37  5027.2   32.38 5027.59   32.43  5027.7   32.44 5027.81   32.45
 5027.89   32.46    5028   32.48  5028.1   32.49  5045.1   34.51  5072.9   34.35
  5102.9   34.17  5128.3    33.8  5138.3   33.65  5201.6   34.48  5258.6    34.6
  5275.2   34.64  5319.5   34.31  5354.6   34.48  5358.2    34.5  5358.3    34.5
    5541   35.27  5548.8    35.3
BR D #Mann= 5
    4304      .1  4968.5    .035  5045.1      .1  5072.9     .14  5548.8      .2
BR D Banks=4968.5,5045.1
BC Design=,, 0 ,, 0 ,,,,,,
BC HTab HWMax=36.02
BC Use User HTab Curves=0
BC User HTab FreeFlow(D)= 0

Type RM Length L Ch R = 1 ,1538.7  ,263.8,261.3,260.6
BEGIN DESCRIPTION:
Downstream Section of Bridge/Culvert/Weir
END DESCRIPTION:
XS GIS Cut Line= 6
      3132583.61     13799335.83      3132952.92     13799348.14
      3133235.61     13799356.62      3133540.92     13799367.92
      3133637.12     13799370.57      3133827.77     13799375.33
#Sta/Elev= 28
    4304   35.85    4364   35.05    4524   35.95  4709.4   34.85  4719.4   34.35
  4746.4   34.52    4827   34.52  4901.3   34.16  4968.5   34.59  4971.1   33.34
  4989.9    26.6  4994.3   25.25  4995.1   21.22  4997.5   20.83  5000.6    20.9
  5003.8   20.87  5004.9   21.04  5007.1   25.27    5009   26.08  5027.1   32.32
  5045.1   34.46  5072.9    34.3  5102.9   34.12  5138.3    33.6  5201.6   34.43
  5275.2   34.59  5319.5   34.26  5548.8   35.25
#Mann= 5 ,-1 , 0
    4304      .1       0  4968.5     .03       0  5045.1      .1       0
  5072.9     .14       0  5548.8      .2       0
#XS Ineff= 2 , 0
       0    4961    35.7    5038       0   35.95
Permanent Ineff=
       F       F
Bank Sta=4968.5,5045.1
XS Rating Curve= 0 ,0
Exp/Cntr=0.5,0.3

Type RM Length L Ch R = 1 ,1277.4  ,409.6,405.7,402.4
BEGIN DESCRIPTION:
Cross Section 1277.4-Interpolated
END DESCRIPTION:
XS GIS Cut Line= 5
      3132872.96      13799595.3      3133064.21     13799566.35
      3133171.39     13799567.82      3133266.82     13799586.91
      3133293.73     13799600.31
#Sta/Elev= 21
  4661.5    35.3    4855    34.8    4955    33.6  4962.2    33.1 4968.49   33.15
 4971.09    31.9 4989.89   25.16 4994.29   23.81 4995.09   19.78 4997.49   19.39
 5000.59   19.46 5003.79   19.43 5004.89    19.6 5007.09   23.83 5008.99   24.64
 5027.19   30.88 5045.09   33.02  5052.2    35.7  5059.5    36.5  5074.9   39.37
  5089.5    42.1
#Mann= 4 , 1 , 0
  4661.5      .1       0 4968.49     .03       0 5045.09      .1       0
  5074.9     .14       0
Bank Sta=4968.49,5045.09
XS Rating Curve= 0 ,0
Exp/Cntr=0.3,0.1

Type RM Length L Ch R = 1 ,871.7   ,123.1,98.5,98.4
BEGIN DESCRIPTION:
Cross Section 871.7-Interpolated
END DESCRIPTION:
XS GIS Cut Line= 6
      3132647.25     13799937.38      3133054.83     13799959.22
      3133165.83      13799975.6      3133245.89     13799977.41
      3133426.02     13799951.94      3133498.81     13799931.93
#Sta/Elev= 25
  4534.1    37.7  4554.1    36.9  4584.1    34.1  4634.1    33.9  4942.3    34.5
  4943.3   33.61  4961.6    29.7  4973.9   29.46  4981.9   26.59  4989.3   18.23
  4997.7   17.17  5006.9   17.45  5010.7   17.89  5022.4   21.93  5025.1   24.71
  5043.6   26.31  5057.9   30.95  5071.3   35.24  5079.4   35.45  5134.5    36.9
  5164.5    37.2  5234.5    40.3  5254.5    42.6  5316.5    43.2    5392    44.4
#Mann= 6 , 1 , 0
  4534.1      .2       0  4534.1      .1       0  4943.3    .045       0
  5071.3      .1       0  5079.4     .14       0    5392      .2       0
Bank Sta=4943.3,5071.3
XS Rating Curve= 0 ,0
Exp/Cntr=0.5,0.3

Type RM Length L Ch R = 1 ,773.2   ,114.3,115,115.8
BEGIN DESCRIPTION:
Upstream Section of Bridge/Culvert/Weir
END DESCRIPTION:
XS GIS Cut Line= 6
       3132689.8     13800056.87      3132807.73     13800074.74
      3132932.47     13800081.75       3133093.6     13800081.88
      3133181.98     13800074.93       3133580.1     13799999.94
#Sta/Elev= 25
  4591.9   35.05  4693.3   33.89  4750.7   33.84  4812.1   34.16  4875.2   35.02
  4921.6   35.13  4943.3   33.06  4961.5   29.15  4973.9   28.91  4981.9   26.04
  4989.3   17.68  4997.7   16.62  5006.9    16.9  5010.7   17.34  5022.4   21.38
  5025.1   24.16  5043.6   25.76  5057.7    30.4  5071.3   34.69  5083.7   35.07
  5160.2   34.51  5308.6    34.6  5407.8   34.61  5484.8   34.46  5491.1   34.45
#Mann= 6 , 1 , 0
  4591.9      .1       0  4943.3    .045       0  5071.3     .14       0
  5308.6      .1       0  5407.8     .14       0  5484.8      .2       0
#XS Ineff= 2 , 0
       0    4928   35.08    5069       0    34.7
Permanent Ineff=
       F       F
Bank Sta=4943.3,5071.3
XS Rating Curve= 0 ,0
Exp/Cntr=0.5,0.3