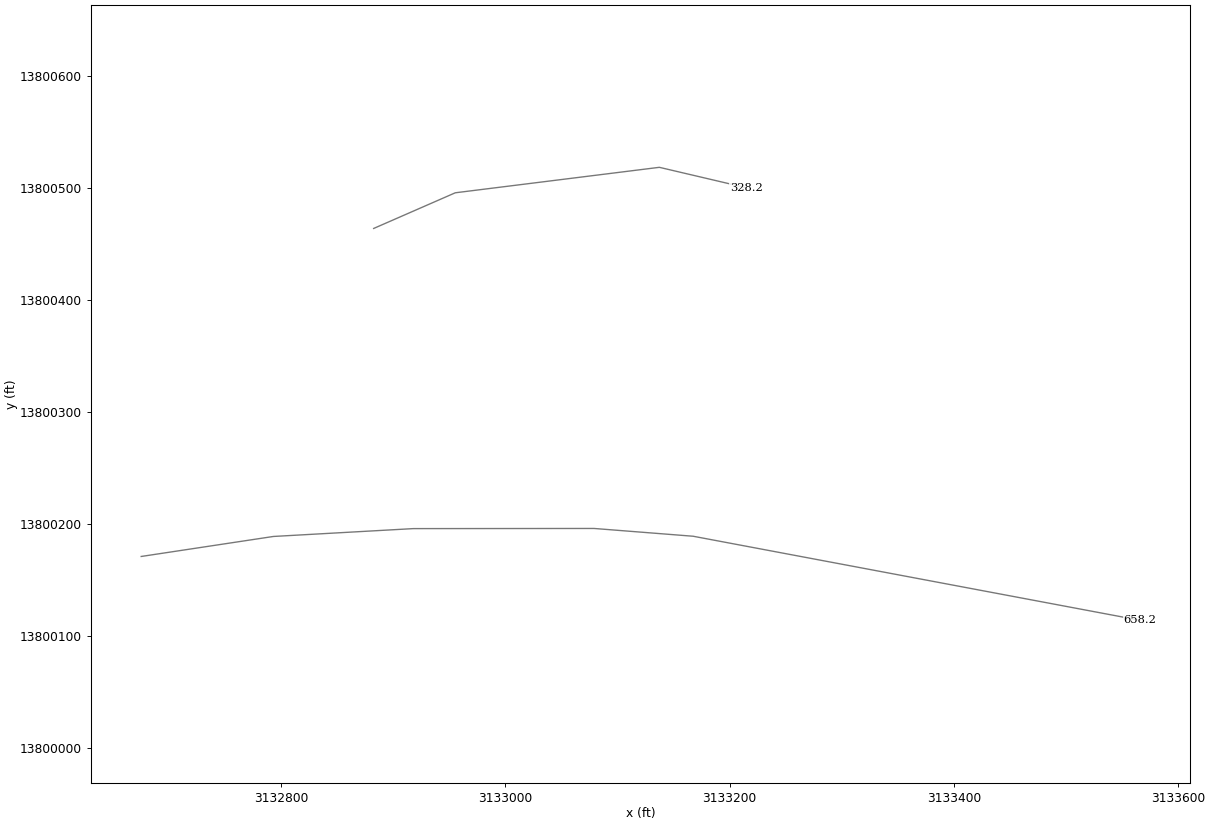
HEC-RAS study C123-00-00.PRJ: C123-00-00

--- C123-00-00.g02 (geometry) --- (continued)

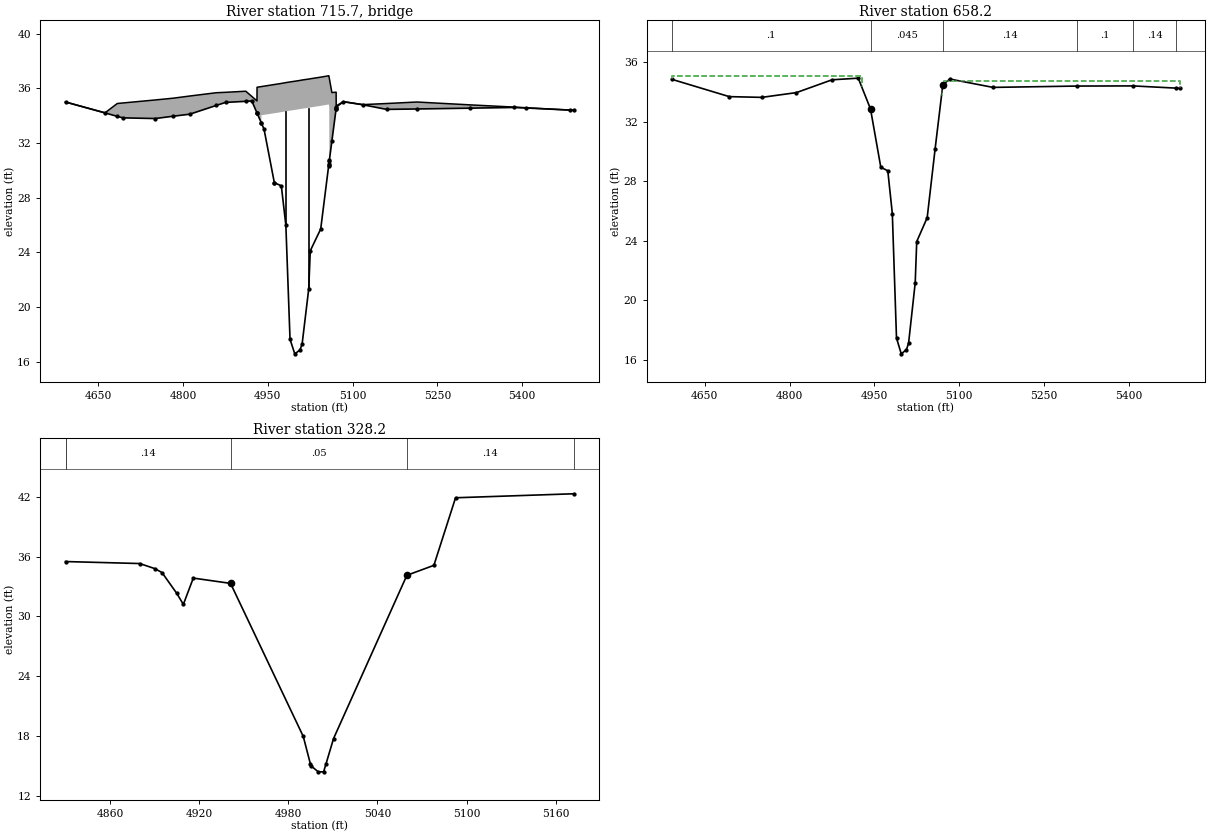
Type RM Length L Ch R = 3 ,715.7   ,,,
BEGIN DESCRIPTION:
AIRPORT BOULEVARD
Structure ID: C23-2
END DESCRIPTION:
Bridge Culvert--1,0,-1,-1, 0
Deck Dist Width WeirC Skew NumUp NumDn MinLoCord MaxHiCord MaxSubmerge Is_Ogee
10,95,2.6,0, 47, 47, , , 0.95, 0, 1,1,,
  4591.9  4661.9  4683.5  4693.3  4750.7  4782.4  4812.1  4858.8  4875.2    4911
  4921.6 4930.79  4930.9 4931.01 4938.61  4938.7  4943.3  4961.5  4961.6  4973.9
  4981.9  4989.3  4997.7  5006.9  5010.7  5022.4  5025.1  5043.6  5057.7  5057.8
    5058 5058.79  5058.9  5063.4 5070.79  5070.9 5071.01  5071.3  5083.7    5118
  5160.2  5213.8  5308.6  5385.3  5407.8  5484.8  5491.1
      35   34.21   34.89   34.93   35.15   35.28   35.44   35.68   35.71   35.79
   35.41   35.08   36.08   36.08   36.13   36.13   36.16   36.28   36.28   36.36
   36.42   36.47   36.52   36.58   36.61   36.68    36.7   36.82   36.92   36.92
   36.92   36.74   36.72   35.69   35.72   35.72   34.72   34.72   35.03   34.81
   34.89      35   34.79   34.63   34.58   34.41    34.4
      35    34.2   33.95   33.84   33.79   33.96   34.11   34.75   34.97   35.05
   35.08    34.2   34.19   34.18   33.46   34.03   34.06   34.18   34.18   34.26
   34.32   34.37   34.42   34.48   34.51   34.58    34.6   34.72   34.82   34.82
   34.82   34.64   30.73   32.15   34.48   34.51   34.55   34.64   35.02    34.8
   34.46   34.49   34.55    34.6   34.56   34.41    34.4
  4591.9  4661.9  4683.5  4693.3  4750.7  4782.4  4812.1  4858.8  4875.2    4911
  4921.6 4930.79  4930.9 4931.01 4938.61  4938.7  4943.3  4961.5  4961.6  4973.9
  4981.9  4989.3  4997.7  5006.9  5010.7  5022.4  5025.1  5043.6  5057.7  5057.8
    5058 5058.79  5058.9  5063.4 5070.79  5070.9 5071.01  5071.3  5083.7    5118
  5160.2  5213.8  5308.6  5385.3  5407.8  5484.8  5491.1
      35   34.21   34.89   34.93   35.15   35.28   35.44   35.68   35.71   35.79
   35.41   35.08   36.08   36.08   36.13   36.13   36.16   36.28   36.28   36.36
   36.42   36.47   36.52   36.58   36.61   36.68    36.7   36.82   36.92   36.92
   36.92   36.74   36.72   35.69   35.72   35.72   34.72   34.72   35.03   34.81
   34.89      35   34.79   34.63   34.58   34.41    34.4
    34.9    34.1   33.85   33.74   33.69   33.86   34.01   34.65   34.87   34.95
   34.98    34.1   34.09   34.08   33.36   33.93   33.96   34.08   34.08   34.16
   34.22   34.27   34.32   34.38   34.41   34.48    34.5   34.62   34.72   34.72
   34.72   34.54   30.63   32.05   34.38   34.41   34.45   34.54   34.92    34.7
   34.36   34.39   34.45    34.5   34.46   34.31    34.3
Pier Skew, UpSta & Num, DnSta & Num=  ,4981.9, 2 ,4981.9, 2 , 0 , 0 , 0 ,,
     1.7     1.7
   24.03   35.33
     1.7     1.7
   23.93   35.23
Pier Skew, UpSta & Num, DnSta & Num=  ,5022.4, 2 ,5022.4, 2 , 0 , 0 , 0 ,,
     1.7     1.7
   20.04   35.59
     1.7     1.7
   19.94   35.49
Abutment Skew #Up #Dn= , 2 , 2
  4938.5  4961.6
   34.03    29.1
  4938.5  4961.6
   33.93      29
Abutment Skew #Up #Dn= , 2 , 2
  5057.9 5058.99
   30.41   34.64
  5057.9 5058.99
   30.31   34.54
BR Coef= 1 , 1 , 0 ,1.25, 0 ,,,0.8,0,2,0,
WSPro=,,,, 1 ,,,, 0 ,,,, 0 ,,,,-1 ,-1 ,-1 , 0 , 0 , 0 , 0 , 0
BR U #Sta/Elev= 47
  4591.9      35  4661.9    34.2  4683.5   33.95  4693.3   33.84  4750.7   33.79
  4782.4   33.96  4812.1   34.11  4858.8   34.75  4875.2   34.97    4911   35.05
  4921.6   35.08 4930.79    34.2  4930.9   34.19 4931.01   34.18 4938.61   33.46
  4938.7   33.45  4943.3   33.01  4961.5    29.1  4961.6    29.1  4973.9   28.86
  4981.9   25.99  4989.3   17.63  4997.7   16.57  5006.9   16.85  5010.7   17.29
  5022.4   21.33  5025.1   24.11  5043.6   25.71  5057.7   30.35  5057.8   30.38
    5058   30.44 5058.79   30.69  5058.9   30.73  5063.4   32.15 5070.79   34.48
  5070.9   34.51 5071.01   34.55  5071.3   34.64  5083.7   35.02    5118    34.8
  5160.2   34.46  5213.8   34.49  5308.6   34.55  5385.3    34.6  5407.8   34.56
  5484.8   34.41  5491.1    34.4
BR U #Mann= 6
  4591.9      .1  4943.3    .045  5071.3     .14  5308.6      .1  5407.8     .14
  5484.8      .2
BR U Banks=4943.3,5071.3
BR D #Sta/Elev= 47
  4591.9    34.9  4661.9    34.1  4683.5   33.85  4693.3   33.74  4750.7   33.69
  4782.4   33.86  4812.1   34.01  4858.8   34.65  4875.2   34.87    4911   34.95
  4921.6   34.98 4930.79    34.1  4930.9   34.09 4931.01   34.08 4938.61   33.36
  4938.7   33.35  4943.3   32.91  4961.5      29  4961.6      29  4973.9   28.76
  4981.9   25.89  4989.3   17.53  4997.7   16.47  5006.9   16.75  5010.7   17.19
  5022.4   21.23  5025.1   24.01  5043.6   25.61  5057.7   30.25  5057.8   30.28
    5058   30.34 5058.79   30.59  5058.9   30.63  5063.4   32.05 5070.79   34.38
  5070.9   34.41 5071.01   34.45  5071.3   34.54  5083.7   34.92    5118    34.7
  5160.2   34.36  5213.8   34.39  5308.6   34.45  5385.3    34.5  5407.8   34.46
  5484.8   34.31  5491.1    34.3
BR D #Mann= 6
  4591.9      .1  4943.3    .045  5071.3     .14  5308.6      .1  5407.8     .14
  5484.8      .2
BR D Banks=4943.3,5071.3
BC Design=,, 0 ,, 0 ,,,,,,
BC HTab HWMax=35.13
BC Use User HTab Curves=0
BC User HTab FreeFlow(D)= 0

Type RM Length L Ch R = 1 ,658.2   ,325.6,330,334.4
BEGIN DESCRIPTION:
Downstream Section of Bridge/Culvert/Weir
END DESCRIPTION:
XS GIS Cut Line= 6
      3132675.24     13800170.95      3132793.17     13800188.82
      3132917.91     13800195.83      3133079.04     13800195.96
      3133167.42     13800189.01      3133565.54     13800114.02
#Sta/Elev= 25
  4591.9   34.84  4693.3   33.68  4750.7   33.63  4812.1   33.95  4875.2   34.81
  4921.6   34.92  4943.3   32.85  4961.5   28.94  4973.9    28.7  4981.9   25.83
  4989.3   17.47  4997.7   16.41  5006.9   16.69  5010.7   17.13  5022.4   21.17
  5025.1   23.95  5043.6   25.55  5057.7   30.19  5071.3   34.48  5083.7   34.86
  5160.2    34.3  5308.6   34.39  5407.8    34.4  5484.8   34.25  5491.1   34.24
#Mann= 6 , 1 , 0
  4591.9      .1       0  4943.3    .045       0  5071.3     .14       0
  5308.6      .1       0  5407.8     .14       0  5484.8      .2       0
#XS Ineff= 2 , 0
       0    4928   35.08    5069       0    34.7
Permanent Ineff=
       F       F
Bank Sta=4943.3,5071.3
XS Rating Curve= 0 ,0
Exp/Cntr=0.5,0.3

Type RM Length L Ch R = 1 ,328.2   ,0,0,0
BEGIN DESCRIPTION:
Cross Section 328.2
END DESCRIPTION:
XS GIS Cut Line= 4
      3132882.53     13800463.88      3132955.31     13800495.73
      3133137.27     13800518.47       3133214.6     13800500.28
#Sta/Elev= 19
  4829.8    35.5  4879.8    35.3  4889.8    34.8  4894.8    34.4  4904.8    32.3
  4909.2    31.2  4915.9   33.84    4941   33.31    4990   17.95  4994.8   15.19
  4995.2      15  5000.1    14.4  5003.7    14.4  5005.2   15.14  5010.4   17.74
  5059.8   34.12    5078   35.12  5092.6    41.9  5172.1    42.3
#Mann= 5 , 1 , 0
  4829.8      .2       0  4829.8     .14       0    4941     .05       0
  5059.8     .14       0  5172.1      .2       0
Bank Sta=4941,5059.8
XS Rating Curve= 0 ,0
Exp/Cntr=0.3,0.1
Stream Node=C123-00-00      ,C123-00-00_0003 , 0 , 0 ,Upstream end
Stream Node=C123-00-00      ,C123-00-00_0003 , 0 , 1 ,Downstream end

Chan Stop Cuts=-1
Use User Specified Reach Order=0
Composite Channel Slope=5

--- C123-00-00.g01 (geometry) ---

Geom Title=C123-00-00 2015
Program Version=4.10

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
River Reach=C123-00-00      ,C123-00-00_0003

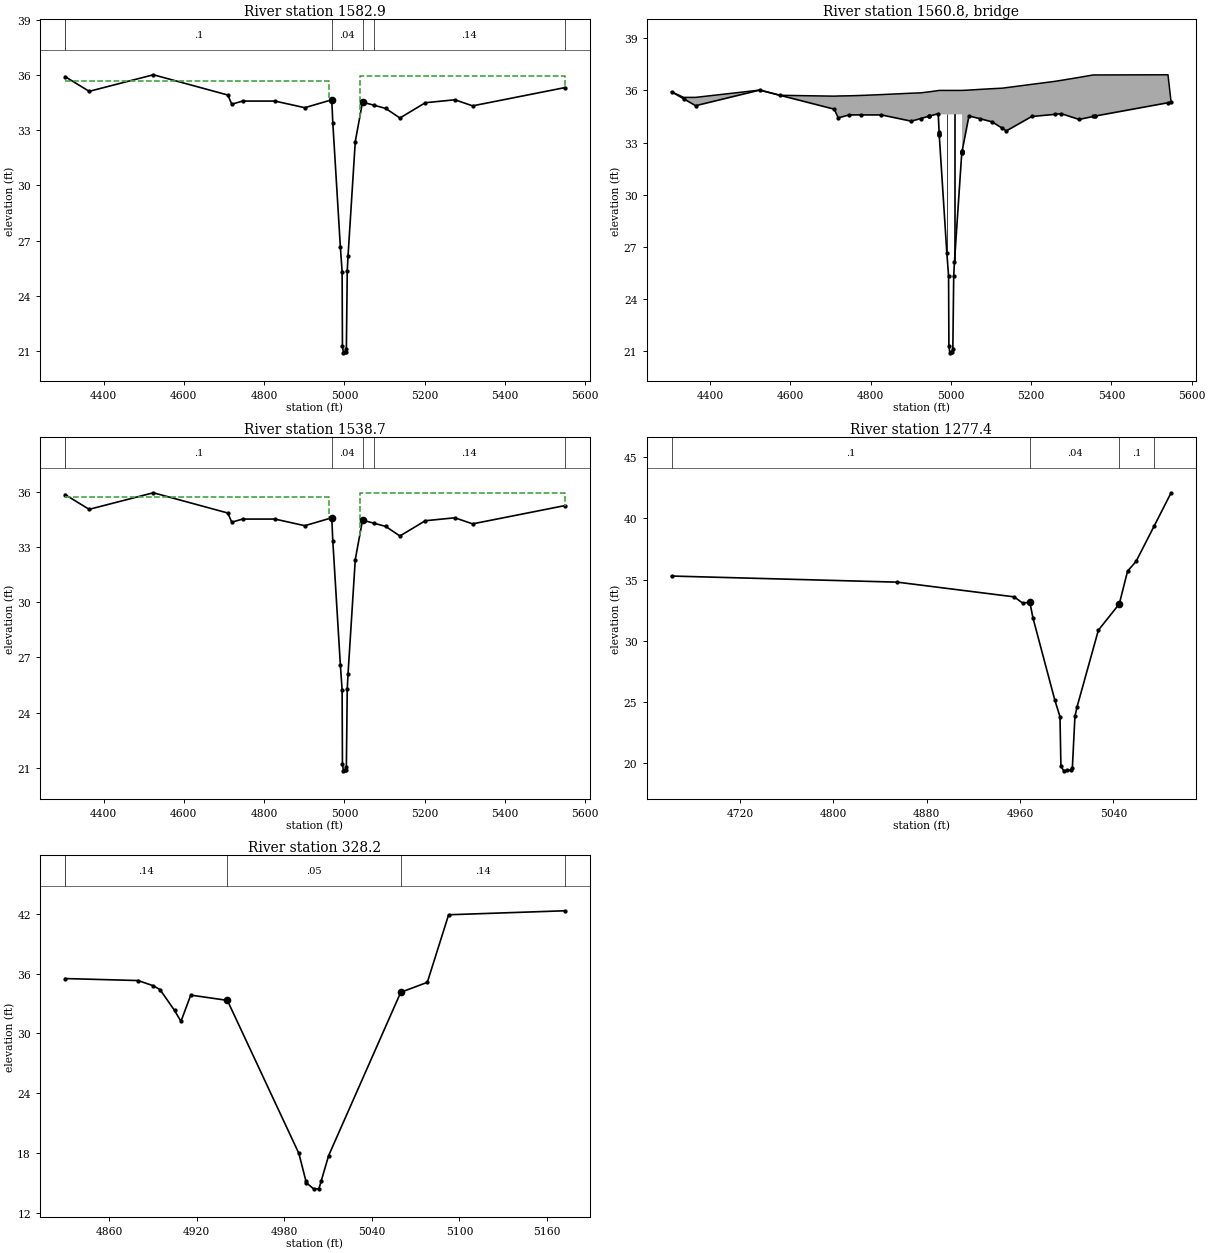
Type RM Length L Ch R = 1 ,1582.9  ,44.8,44.2,43.9
BEGIN DESCRIPTION:
Upstream Section of Bridge/Culvert/Weir
END DESCRIPTION:
XS GIS Cut Line= 6
      3132593.68     13799292.79      3132962.98      13799305.1
      3133245.67     13799313.58      3133550.98     13799324.88
      3133647.18     13799327.53      3133837.84      13799332.3
#Sta/Elev= 28
    4304   35.92    4364   35.12    4524   36.02  4709.4   34.92  4719.4   34.42
  4746.4   34.59    4827   34.59  4901.3   34.23  4968.5   34.66  4971.1   33.41
  4989.9   26.67  4994.3   25.32  4995.1   21.29  4997.5    20.9  5000.6   20.97
  5003.8   20.94  5004.9   21.11  5007.1   25.34    5009   26.15  5027.1   32.39
  5045.1   34.53  5072.9   34.37  5102.9   34.19  5138.3   33.67  5201.6    34.5
  5275.2   34.66  5319.5   34.33  5548.8   35.32
#Mann= 6 , 1 , 0
    4304      .2       0    4304      .1       0  4968.5     .04       0
  5045.1      .1       0  5072.9     .14       0  5548.8      .2       0
#XS Ineff= 2 , 0
       0    4961    35.7    5038       0   35.95
Permanent Ineff=
       F       F
Bank Sta=4968.5,5045.1
XS Rating Curve= 0 ,0
Exp/Cntr=0.5,0.3

Type RM Length L Ch R = 3 ,1560.8  ,,,
BEGIN DESCRIPTION:
SOUTH ACRES
Structure ID: C23-3
END DESCRIPTION:
Bridge Culvert--1,0,-1,-1, 0
Deck Dist Width WeirC Skew NumUp NumDn MinLoCord MaxHiCord MaxSubmerge Is_Ogee
10,24.2,2.6,0, 52, 52, , , 0.95, 0, 1,1,,
    4304  4334.1    4364    4524  4574.1  4709.4  4719.4  4746.4  4775.4    4827
  4901.3  4924.7 4945.99  4946.1 4946.21  4968.5  4970.7 4970.81  4970.9    4971
  4971.1  4989.9  4994.3  4995.1  4997.5  5000.6  5003.8  5004.9  5007.1    5009
  5027.1  5027.2 5027.59  5027.7 5027.81 5027.89    5028  5028.1  5045.1  5072.9
  5102.9  5128.3  5138.3  5201.6  5258.6  5275.2  5319.5  5354.6  5358.2  5358.3
    5541  5548.8
   35.92    35.6    35.6   36.02   35.72   35.67   35.68   35.69   35.71   35.76
   35.84   35.86   35.92   35.92   35.92   35.99      36      36      36      36
      36      36      36      36      36      36      36      36      36      36
      36      36      36      36      36      36      36      36   36.02   36.06
    36.1   36.13   36.16   36.35   36.52   36.58   36.75   36.89   36.89   36.89
    36.9   35.32
   35.92   35.52   35.12   36.02   35.72   34.92   34.42   34.59   34.59   34.59
   34.23   34.38   34.52   34.52   34.52   34.66    33.6   33.55   34.62   34.62
   34.62   34.62   34.62   34.62   34.62   34.62   34.62   34.62   34.62   34.62
   34.62   34.62   34.62   34.62   34.62   34.62    32.5   32.51   34.53   34.37
   34.19   33.82   33.67    34.5   34.62   34.66   34.33    34.5   34.52   34.52
   35.29   35.32
    4304  4334.1    4364    4524  4574.1  4709.4  4719.4  4746.4  4775.4    4827
  4901.3  4924.7 4945.99  4946.1 4946.21  4968.5  4970.7 4970.81  4970.9    4971
  4971.1  4989.9  4994.3  4995.1  4997.5  5000.6  5003.8  5004.9  5007.1    5009
  5027.1  5027.2 5027.59  5027.7 5027.81 5027.89    5028  5028.1  5045.1  5072.9
  5102.9  5128.3  5138.3  5201.6  5258.6  5275.2  5319.5  5354.6  5358.2  5358.3
    5541  5548.8
    35.9    35.6    35.6   36.01   35.71   35.67   35.68   35.69   35.71   35.76
   35.84   35.86   35.92   35.92   35.92   35.99      36      36      36      36
      36      36      36      36      36      36      36      36      36      36
      36      36      36      36      36      36      36      36   36.02   36.06
    36.1   36.13   36.16   36.35   36.52   36.58   36.75   36.89   36.89   36.89
    36.9    35.3
    35.9    35.5    35.1      36    35.7    34.9    34.4   34.57   34.57   34.57
   34.21   34.36    34.5    34.5    34.5   34.64   33.58   33.53    34.6    34.6
    34.6    34.6    34.6    34.6    34.6    34.6    34.6    34.6    34.6    34.6
    34.6    34.6    34.6    34.6    34.6    34.6   32.48   32.49   34.51   34.35
   34.17    33.8   33.65   34.48    34.6   34.64   34.31   34.48    34.5    34.5
   35.27    35.3
Pier Skew, UpSta & Num, DnSta & Num=  ,4989.9, 2 ,4989.9, 2 , 0 , 0 , 0 ,,
     1.2     1.2
   25.49   35.62
     1.2     1.2
   25.47    35.6
Pier Skew, UpSta & Num, DnSta & Num=  ,5009, 2 ,5009, 2 , 0 , 0 , 0 ,,
     1.2     1.2
   24.89   35.62
     1.2     1.2
   24.87    35.6
BR Coef= 1 , 1 , 0 ,1.25, 0 ,,,0.8,0,2,0,
WSPro=,,,, 1 ,,,, 0 ,,,, 0 ,,,,-1 ,-1 ,-1 , 0 , 0 , 0 , 0 , 0
BR U #Sta/Elev= 52
    4304   35.92  4334.1   35.52    4364   35.12    4524   36.02  4574.1   35.72
  4709.4   34.92  4719.4   34.42  4746.4   34.59  4775.4   34.59    4827   34.59
  4901.3   34.23  4924.7   34.38 4945.99   34.52  4946.1   34.52 4946.21   34.52
  4968.5   34.66  4970.7    33.6 4970.81   33.55  4970.9   33.51    4971   33.46
  4971.1   33.41  4989.9   26.67  4994.3   25.32  4995.1   21.29  4997.5    20.9
  5000.6   20.97  5003.8   20.94  5004.9   21.11  5007.1   25.34    5009   26.15
  5027.1   32.39  5027.2    32.4 5027.59   32.45  5027.7   32.46 5027.81   32.47
 5027.89   32.48    5028    32.5  5028.1   32.51  5045.1   34.53  5072.9   34.37
  5102.9   34.19  5128.3   33.82  5138.3   33.67  5201.6    34.5  5258.6   34.62
  5275.2   34.66  5319.5   34.33  5354.6    34.5  5358.2   34.52  5358.3   34.52
    5541   35.29  5548.8   35.32
BR U #Mann= 6
    4304      .2    4304      .1  4968.5     .04  5045.1      .1  5072.9     .14
  5548.8      .2
BR U Banks=4968.5,5045.1
BR D #Sta/Elev= 52
    4304    35.9  4334.1    35.5    4364    35.1    4524      36  4574.1    35.7
  4709.4    34.9  4719.4    34.4  4746.4   34.57  4775.4   34.57    4827   34.57
  4901.3   34.21  4924.7   34.36 4945.99    34.5  4946.1    34.5 4946.21    34.5
  4968.5   34.64  4970.7   33.58 4970.81   33.53  4970.9   33.49    4971   33.44
  4971.1   33.39  4989.9   26.65  4994.3    25.3  4995.1   21.27  4997.5   20.88
  5000.6   20.95  5003.8   20.92  5004.9   21.09  5007.1   25.32    5009   26.13
  5027.1   32.37  5027.2   32.38 5027.59   32.43  5027.7   32.44 5027.81   32.45
 5027.89   32.46    5028   32.48  5028.1   32.49  5045.1   34.51  5072.9   34.35
  5102.9   34.17  5128.3    33.8  5138.3   33.65  5201.6   34.48  5258.6    34.6
  5275.2   34.64  5319.5   34.31  5354.6   34.48  5358.2    34.5  5358.3    34.5
    5541   35.27  5548.8    35.3
BR D #Mann= 6
    4304      .2    4304      .1  4968.5     .04  5045.1      .1  5072.9     .14
  5548.8      .2
BR D Banks=4968.5,5045.1
BC Design=,, 0 ,, 0 ,,,,,,
BC HTab HWMax=36.02
BC Use User HTab Curves=0
BC User HTab FreeFlow(D)= 0

Type RM Length L Ch R = 1 ,1538.7  ,263.8,261.3,260.6
BEGIN DESCRIPTION:
Downstream Section of Bridge/Culvert/Weir
END DESCRIPTION:
XS GIS Cut Line= 6
      3132583.61     13799335.83      3132952.92     13799348.14
      3133235.61     13799356.62      3133540.92     13799367.92
      3133637.12     13799370.57      3133827.77     13799375.33
#Sta/Elev= 28
    4304   35.85    4364   35.05    4524   35.95  4709.4   34.85  4719.4   34.35
  4746.4   34.52    4827   34.52  4901.3   34.16  4968.5   34.59  4971.1   33.34
  4989.9    26.6  4994.3   25.25  4995.1   21.22  4997.5   20.83  5000.6    20.9
  5003.8   20.87  5004.9   21.04  5007.1   25.27    5009   26.08  5027.1   32.32
  5045.1   34.46  5072.9    34.3  5102.9   34.12  5138.3    33.6  5201.6   34.43
  5275.2   34.59  5319.5   34.26  5548.8   35.25
#Mann= 6 , 1 , 0
    4304      .2       0    4304      .1       0  4968.5     .04       0
  5045.1      .1       0  5072.9     .14       0  5548.8      .2       0
#XS Ineff= 2 , 0
       0    4961    35.7    5038       0   35.95
Permanent Ineff=
       F       F
Bank Sta=4968.5,5045.1
XS Rating Curve= 0 ,0
Exp/Cntr=0.5,0.3

Type RM Length L Ch R = 1 ,1277.4  ,409.6,405.7,402.4
BEGIN DESCRIPTION:
Cross Section 1277.4-Interpolated
END DESCRIPTION:
XS GIS Cut Line= 5
      3132872.96      13799595.3      3133064.21     13799566.35
      3133171.39     13799567.82      3133266.82     13799586.91
      3133293.73     13799600.31
#Sta/Elev= 21
  4661.5    35.3    4855    34.8    4955    33.6  4962.2    33.1 4968.49   33.15
 4971.09    31.9 4989.89   25.16 4994.29   23.81 4995.09   19.78 4997.49   19.39
 5000.59   19.46 5003.79   19.43 5004.89    19.6 5007.09   23.83 5008.99   24.64
 5027.19   30.88 5045.09   33.02  5052.2    35.7  5059.5    36.5  5074.9   39.37
  5089.5    42.1
#Mann= 4 , 1 , 0
  4661.5      .1       0 4968.49     .04       0 5045.09      .1       0
  5074.9     .14       0
Bank Sta=4968.49,5045.09
XS Rating Curve= 0 ,0
Exp/Cntr=0.3,0.1

Type RM Length L Ch R = 1 ,328.2   ,0,0,0
BEGIN DESCRIPTION:
Cross Section 328.2
END DESCRIPTION:
XS GIS Cut Line= 4
      3132882.53     13800463.88      3132955.31     13800495.73
      3133137.27     13800518.47       3133214.6     13800500.28
#Sta/Elev= 19
  4829.8    35.5  4879.8    35.3  4889.8    34.8  4894.8    34.4  4904.8    32.3
  4909.2    31.2  4915.9   33.84    4941   33.31    4990   17.95  4994.8   15.19
  4995.2      15  5000.1    14.4  5003.7    14.4  5005.2   15.14  5010.4   17.74
  5059.8   34.12    5078   35.12  5092.6    41.9  5172.1    42.3
#Mann= 5 , 1 , 0
  4829.8      .2       0  4829.8     .14       0    4941     .05       0
  5059.8     .14       0  5172.1      .2       0
Bank Sta=4941,5059.8
XS Rating Curve= 0 ,0
Exp/Cntr=0.3,0.1